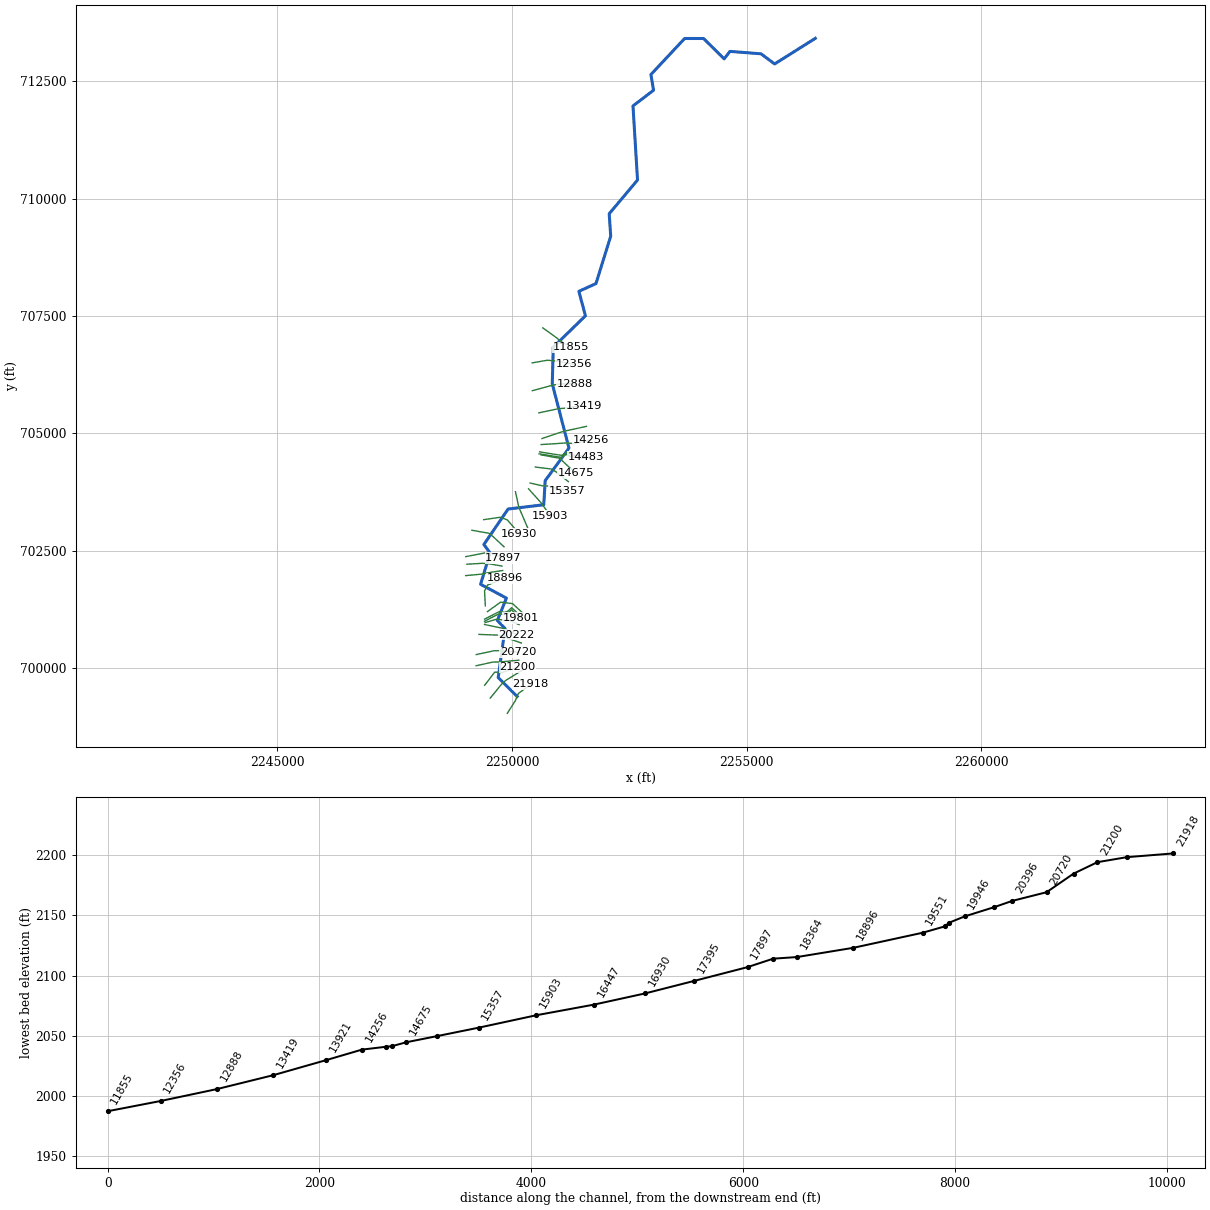
--- BIGLAURLRN.prj (project) ---

Proj Title=BIGLAURLRN
Current Plan=p01
Default Exp/Contr=0,0
English Units
Geom File=g01
Flow File=f01
Plan File=p01
BEGIN DESCRIPTION:
----------MODEL BY WOOD PLC 2022----------
AFH study
Randolph County, WV
HEC-RAS Version: RAS 6.2
Vertical Datum: NAVD88
Projection: NAD 1983 StatePlane West Virginia S FIPS 4702 (US Feet)
Terrain: 1-meter LIDAR (FEMA Region III 3DEP collected 2016-2018)
Land Use: 2019 NLCD
Hydrologic Method:
WV SIR2010-5033 regression equations
Additional Model Notes:
None
END DESCRIPTION:
DSS Export Rating Curves= 0
DSS Export Rating Curve Sorted= 0
DSS Export Volume Flow Curves= 0
DXF OffsetX= 0
DXF OffsetY= 0
DXF ScaleX= 0
DXF ScaleY= 0

--- BIGLAURLRN.p01 (plan) ---

Plan Title=Floodplain
Program Version=6.20
Short Identifier=Floodplain
Geom File=g01
Flow File=f01
Subcritical Flow
K Sum by GR= 0
Std Step Tol= 0.01
Critical Tol= 0.01
Num of Std Step Trials= 20
Max Error Tol= 0.3
Flow Tol Ratio= 0.001
Split Flow NTrial= 30
Split Flow Tol= 0.02
Split Flow Ratio= 0.02
Log Output Level= 0
Friction Slope Method= 1
Unsteady Friction Slope Method= 2
Unsteady Bridges Friction Slope Method= 1
Parabolic Critical Depth
Global Vel Dist= 0 , 0 , 0
Global Log Level= 0
CheckData=True
Encroach Param=-1 ,0,0, 0
Mapping Interval=1HOUR
Computation Time Step Use Courant=        0
Computation Time Step Use Time Series=    0
Computation Time Step Count To Double=0
Computation Time Step Max Doubling=0
Computation Time Step Max Halving=0
Computation Time Step Residence Courant=0
Run HTab= 0
Run UNet= 0
Run Sediment= 0
Run PostProcess= 0
Run WQNet= 0
Run RASMapper=-1
UNET Theta= 0
UNET Theta Warmup= 0
UNET ZTol= 0
UNET ZSATol= 0
UNET MxIter= 0
UNET Max Iter WO Improvement= 0
UNET MaxInSteps= 0
UNET DtIC= 0
UNET DtMin= 0
UNET MaxCRTS= 0
UNET WFStab= 0
UNET SFStab= 0
UNET WFX= 1
UNET SFX= 1
UNET Gravity=32.174
UNET 1D Methodology=Finite Difference
UNET DSS MLevel= 1
UNET Pardiso=0
UNET DZMax Abort= 0
UNET Use Existing IB Tables= 0
UNET Froude Reduction=False
UNET Froude Limit= 0
UNET Froude Power= 0
UNET D1 Cores= 0
UNET WindReference=Eulerian
UNET WindDragFormulation=Hsu (1988)
UNET D2 Coriolis=0
UNET D2 Cores= 0
UNET D2 Theta= 1
UNET D2 Theta Warmup= 1
UNET D2 Z Tol= 0.01
UNET D2 Volume Tol= 0.01
UNET D2 Max Iterations= 20
UNET D2 Equation= 0
UNET D2 RampUpFraction=0.1
UNET D2 TimeSlices= 1
UNET D2 Turbulence Formulation=Non-Conservative (original)
UNET D2 Eddy Viscosity=0.3
UNET D2 Transverse Eddy Viscosity=0.1
UNET D2 Smagorinsky Mixing=0
UNET D2 BCVolumeCheck=0
UNET D2 Cores=0
UNET D2 SolverType=PARDISO (Direct)
UNET D2 Minimum Iterations= 2147483647
UNET D2 Maximum Iterations= 2147483647
UNET D2 Restart Number= 10
UNET D2 Relaxation Coeff=1.3
UNET D2 SOR Precondition Iterations= 10
UNET D2 ILUT Maximum Fill= 8
UNET D2 ILUT Tolerance=1E-08
UNET D1D2 MaxIter= 0
UNET D1D2 ZTol=0.01
UNET D1D2 QTol=0.1
UNET D1D2 MinQTol=1
Write IC File= 0
Write IC File at Fixed DateTime=0
Write IC File at Sim End=0
Echo Input=False
Echo Parameters=False
Echo Output=False
Write Detailed= 0
HDF Write Warmup=0
HDF Write Time Slices=0
HDF Flush=0
HDF Compression= 1
HDF Chunk Size= 1
HDF Spatial Parts= 1
HDF Use Max Rows=0
HDF Fixed Rows= 1
Calibration Method= 0
Calibration Iterations= 20
Calibration Max Change=0.05
Calibration Tolerance=0.2
Calibration Maximum=1.5
Calibration Minimum=0.5
Calibration Optimization Method= 1
WQ AD Non Conservative
WQ ULTIMATE=-1
WQ Max Comp Step=1HOUR
WQ Output Interval=15MIN
WQ Output Selected Increments= 0
WQ Output face flow=0
WQ Output face velocity=0
WQ Output face area=0
WQ Output face dispersion=0
WQ Output cell volume=0
WQ Output cell surface area=0
WQ Output cell continuity=0
WQ Output cumulative cell continuity=0
WQ Output face conc=0
WQ Output face dconc_dx=0
WQ Output face courant=0
WQ Output face peclet=0
WQ Output face adv mass=0
WQ Output face disp mass=0
WQ Output cell mass=0
WQ Output cell source sink temp=0
WQ Output nsm pathways=0
WQ Output nsm derived pathways=0
WQ Create Restart=0
WQ Fixed Restart=0
WQ System Summary=0
WQ Write To DSS=0
Sorting and Armoring Iterations= 10
XS Update Threshold= 0.02
Bed Roughness Predictor= 0
Hydraulics Update Threshold= 0.02
Energy Slope Method= 1
Volume Change Method= 1
Sediment Retention Method= 0
Sediment TS Multiplier= 1
Warm Up Method= 0
XS Weighting Method= 0
Number of US Weighted Cross Sections= 1
Number of DS Weighted Cross Sections= 1
Upstream XS Weight=0
Main XS Weight=1
Downstream XS Weight=0
Number of DS XS's Weighted with US Boundary= 1
Upstream Boundary Weight= 1
Weight of XSs Associated with US Boundary= 0
Number of US XS's Weighted with DS Boundary= 1
Downstream Boundary Weight= 0.5
Weight of XSs Associated with DS Boundary= 0.5
Percentile Method= 0
Sediment Output Level= 3
Mass or Volume Output= 0
Output Increment Type= 1
Profile and TS Output Increment= 1
Transport Output Increment 1
XS Output Flag= 0
XS Output Increment= 10
Read HDF5 Sediment Hotstart= 0
Sediment Hotstart Type= 0
Write Gradation File= 0
Read Gradation Hotstart= 0
Write HDF5 File= 1
Write Binary Output= 1
Write DSS Sediment File= 0
DSS Sediment Output Type= 1
SV Curve= 0
Specific Gage Flag= 0
Subcell Erosion Methods= 0
Subcell Deposition Methods= 0
Advection Scheme= 1
Matrix Solver= 0
Implicit Weighting Factor= 1
Maximum Outer Loop Convergence Iterations= 5
Convergence Maximum Absolute= 0.001
Convergence RMSE= 0.0001
Grain Fractions Max Abs Error= 0.001
Max Subgrid Regions= 1
Max Subgrid Length Scale= 3.402823E+38
Initial Layer Thickness= 3.402823E+38
Min Layer Thickness= 3.402823E+38
Max Layer Thickness= 3.402823E+38
Number of Layers= 5

--- BIGLAURLRN.f01 (steady flow) ---

Flow Title=Flow
Program Version=6.20
Number of Profiles= 1
Profile Names=P100yr
River Rch & RM=BIGLAURLRN,Main,21918
     393
River Rch & RM=BIGLAURLRN,Main,18896
     477
River Rch & RM=BIGLAURLRN,Main,16930
     651
River Rch & RM=BIGLAURLRN,Main,16447
     724
River Rch & RM=BIGLAURLRN,Main,11855
     821
River Rch & RM=BIGLAURLRN,Main,8918
     921
River Rch & RM=BIGLAURLRN,Main,4006
    1350
Boundary for River Rch & Prof#=BIGLAURLRN,Main            , 1
Up Type= 0
Dn Type= 3
Dn Slope=0.02911
DSS Import GetInterval= 0
DSS Import GetPeak= 0
DSS Import FillOption= 0

--- BIGLAURLRN.g01 (geometry) ---

Geom Title=Geometry
Program Version=6.20

River Reach=BIGLAURLRN      ,Main
Reach XY= 30
     2250111.535      699389.696     2249707.788      699792.803
     2249852.681      700839.696     2249689.661      701009.488
     2249882.575      701485.997     2249332.543      701780.391
     2249534.626      702449.141     2249402.506      702628.369
     2249917.764      703384.236     2250678.365      703475.841
     2250707.819      703988.349     2251214.616      704684.355
      2250859.04      706053.827     2250880.768      706833.974
     2251565.586      707502.077     2251426.132      708023.721
2251789.61088699708188.671813245     2252103.844      709199.394
2252071.43773919709677.284545092     2252675.055      710395.464
     2252578.157      711975.457     2253016.044      712309.084
     2252960.376      712644.478     2253678.288      713412.585
     2254083.042      713411.959     2254519.337      712977.708
      2254643.31 713137.346456942255305.47512946713085.907095456
     2255594.584      712869.872     2256462.179      713415.683

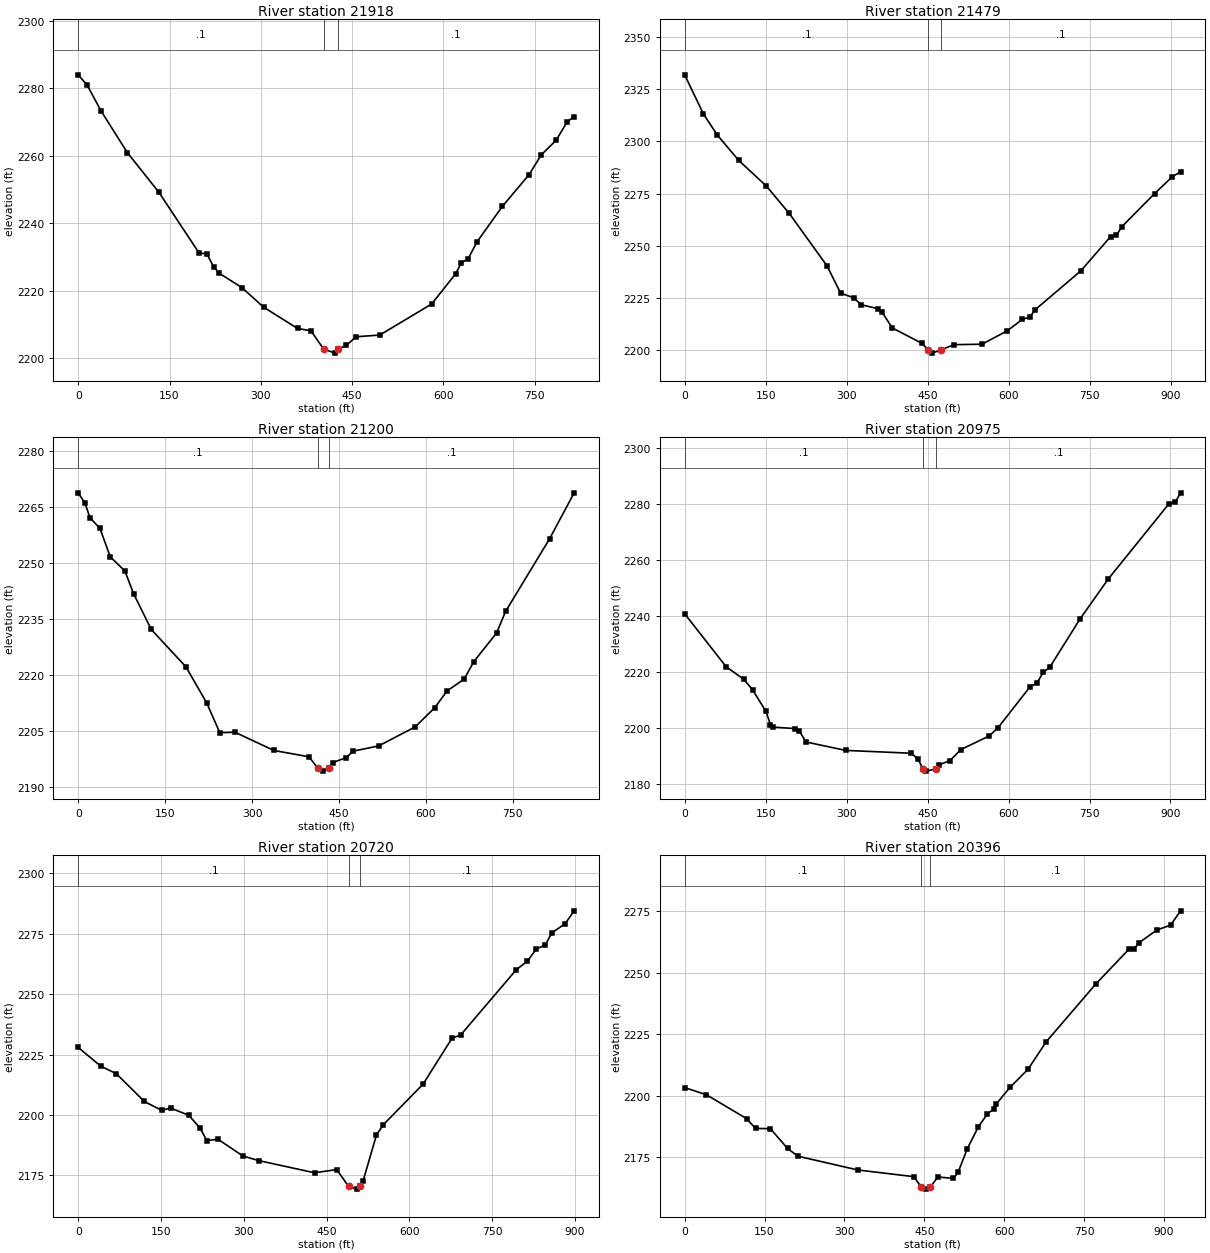
Type RM Length L Ch R = 1 ,21918   ,445.6,438.6,433.3
XS GIS Cut Line= 4
2249900.39821383699029.5111103132250072.84277672699299.698078162
2250136.43480386699452.0895651952250399.96912337 699649.10497386
#Sta/Elev= 30
       0 2283.95    14.5 2280.95    37.3 2273.33    80.7 2260.91   132.5 2249.17
   198.9 2231.09     211 2231.01   222.6 2227.06   231.3 2225.23     269 2220.92
   304.4 2215.15   360.3 2208.83   382.3 2208.13  403.17 2202.73   421.8 2201.52
  426.992202.729   440.4  2203.8   456.5 2206.38   495.3 2206.86   580.6 2216.07
   620.2 2225.06   629.1 2228.18   640.6 2229.51   655.1 2234.47   696.6 2244.95
   740.6 2254.37   760.6 2260.23     785 2264.55   803.5 2270.08   814.7 2271.58
#Mann= 3 ,-1,0
       0      .1       0  403.17    .045       0  426.99      .1       0
Bank Sta=403.17,426.99
XS Rating Curve= 0 ,0
Exp/Cntr=0.3,0.1

Type RM Length L Ch R = 1 ,21479   ,283.7,278.9,271.3
XS GIS Cut Line= 4
     2249538.131      699354.4462249804.52510275699682.482927022
2249882.78078466699740.6453204482250221.15098791699950.568146582
#Sta/Elev= 30
       0 2331.99    34.7  2313.2    60.3 2303.13   100.1  2290.9   151.3  2278.6
   193.6 2265.47   263.4 2240.36   288.8  2227.2   313.3 2224.95   326.8 2221.62
   358.6  2219.7   364.9 2218.27   384.4 2210.52   438.6  2203.2  451.28 2199.95
   458.6 2198.41  474.372199.949   498.6 2202.47   550.5 2202.69     597 2209.08
   625.3  2214.6   639.4 2215.81   648.8 2219.21   733.6 2237.91   788.7 2254.36
   799.5 2254.97   809.4 2259.07   870.1 2275.01     903 2283.08   918.3 2285.52
#Mann= 3 ,-1,0
       0      .1       0  451.28    .045       0  474.37      .1       0
Bank Sta=451.28,474.37
XS Rating Curve= 0 ,0
Exp/Cntr=0.3,0.1

Type RM Length L Ch R = 1 ,21200   ,224.6,225.1,225.4
XS GIS Cut Line= 4
2249419.41210367699629.3410412982249633.52059064699908.293812891
 2249797.4665178699903.3999046182250120.46446386700009.842409568
#Sta/Elev= 30
       0 2268.79    11.8 2266.03    20.4 2262.11    37.5 2259.32    55.3 2251.67
    80.5  2247.9    95.6 2241.78   126.1  2232.2   185.9 2222.19   221.7 2212.53
   244.3 2204.55   270.6 2204.66   337.6 2199.78   398.3 2198.08  413.242195.075
   422.3 2194.24  431.932195.076   438.9 2196.53   462.4 2197.85   474.4 2199.59
   518.5    2201   581.7 2206.12   615.4 2211.27   636.4 2215.72   665.9 2218.89
   682.8 2223.62     722 2231.28   737.5 2237.06   813.3 2256.48   855.8 2268.83
#Mann= 3 ,-1,0
       0      .1       0  413.24    .045       0  431.93      .1       0
Bank Sta=413.24,431.93
XS Rating Curve= 0 ,0
Exp/Cntr(USF)=0,0
Exp/Cntr=0.3,0.1

Type RM Length L Ch R = 1 ,20975   ,257,255.5,255.6
XS GIS Cut Line= 4
2249237.00792316700044.3500305652249586.50670698700121.497150059
2249766.35783603700127.6145354012250145.63572722700163.095370383
#Sta/Elev= 30
       0 2240.91      77 2221.95   109.7  2217.5   126.1 2213.65   150.7 2206.03
   158.9 2201.32     163 2200.44     204 2199.93   212.2 2199.09   224.8 2195.13
   298.2 2192.12   419.6 2191.11   431.6 2189.19  441.682185.526   447.6 2184.72
  465.672185.527   471.8    2187   491.7 2188.51   511.7 2192.42   563.8 2197.25
   579.9 2200.07   640.1  2214.9   652.2 2216.05   664.2 2219.97   676.3  2221.8
   732.5 2239.07   784.8 2253.35   897.2 2280.21   909.3 2280.91   918.8 2284.11
#Mann= 3 ,-1,0
       0      .1       0  441.68    .045       0  465.67      .1       0
Bank Sta=441.68,465.67
XS Rating Curve= 0 ,0
Exp/Cntr(USF)=0,0
Exp/Cntr=0.3,0.1

Type RM Length L Ch R = 1 ,20720   ,324.9,323,320.1
XS GIS Cut Line= 4
2249240.51990655700282.5551839742249618.89671366700363.974340452
2249775.10724848700366.3402466212250128.39379639700330.311588204
#Sta/Elev= 30
       0 2227.93    40.6  2220.2    69.2 2217.03   119.8 2205.54     151 2201.89
   167.4  2202.8   200.1 2199.87   220.8 2194.55   232.9 2189.37   253.3  2189.9
   298.3 2182.97     327 2181.06   428.3 2176.02   468.4 2177.34  489.742170.398
   504.3 2169.25  510.962170.396   516.3 2172.82   540.3 2191.68   552.4 2195.85
   624.8 2212.75     677 2231.69   693.1 2233.16   793.6 2260.12   813.7 2263.65
   829.9 2268.73   845.9 2270.28     858  2275.4   882.1 2279.16   898.4  2284.5
#Mann= 3 ,-1,0
       0      .1       0  489.74    .045       0  510.96      .1       0
Bank Sta=489.74,510.96
XS Rating Curve= 0 ,0
Exp/Cntr=0.3,0.1

Type RM Length L Ch R = 1 ,20396   ,177,174.9,174.6
XS GIS Cut Line= 4
     2249299.259      700712.6472249697.90202781700697.512466091
2249783.40509788700676.383614421     2250202.084       700527.78
#Sta/Elev= 30
       0 2203.31    40.9 2200.39   116.1 2190.72     133 2186.73     161 2186.61
   193.2 2178.58   212.5 2175.45   325.1 2169.84   430.1 2167.13  444.59 2162.82
   453.9 2162.06  461.132162.821   475.4    2167   504.8 2166.42   513.3 2168.83
   530.8 2178.52   551.5  2187.4   568.5 2192.62     581 2194.73   585.4 2196.72
   610.9 2203.41   644.9  2210.8   678.8  2221.9   772.2 2245.44   834.7 2259.64
   844.4  2259.8   852.8 2262.09   886.8 2267.36   912.3 2269.29   931.3 2275.13
#Mann= 3 ,-1,0
       0      .1       0  444.59    .045       0  461.13      .1       0
Bank Sta=444.59,461.13
XS Rating Curve= 0 ,0
Exp/Cntr=0.3,0.1

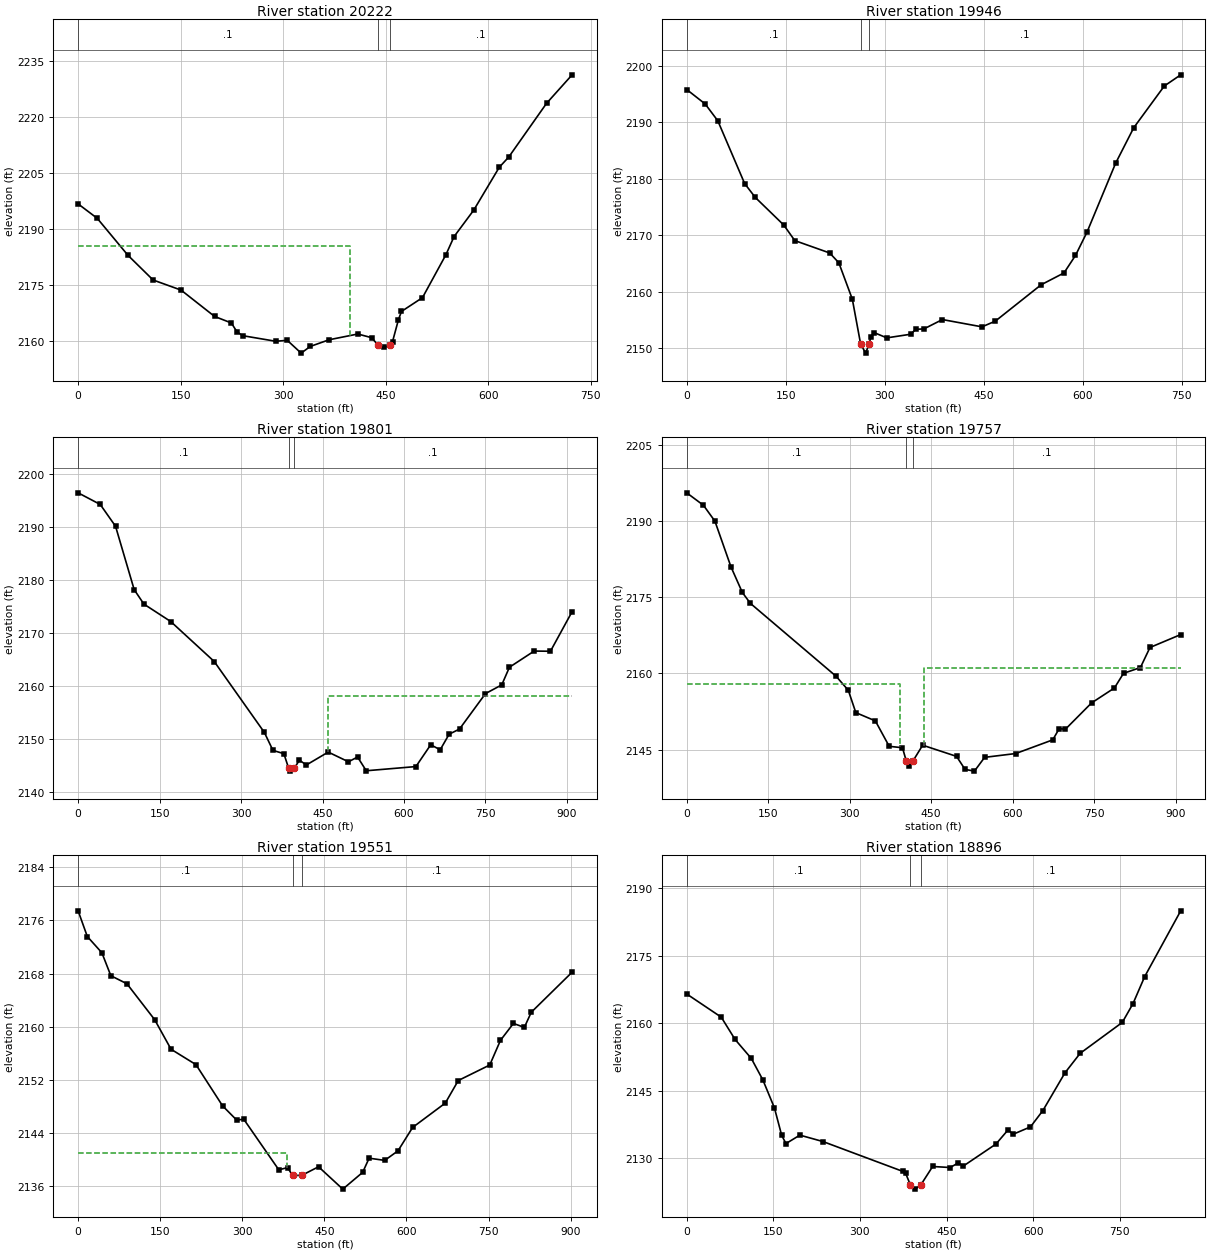
Type RM Length L Ch R = 1 ,20222   ,275,275.9,284.8
XS GIS Cut Line= 4
2249416.73736512700923.5212115392249820.31282122700839.379162475
 2249888.2142054700810.1001079562250102.41061856700709.902115398
#Sta/Elev= 30
       0  2196.7      28 2192.83      73 2182.92   109.7 2176.32   150.6 2173.62
   199.6 2166.57   224.2 2164.81   232.3 2162.47   240.5 2161.42   288.9 2159.92
     306 2160.16   326.3 2156.74   339.6 2158.53   367.2 2160.32   409.2 2161.86
   429.5 2160.87  438.842158.873     447 2158.28  456.812158.873     460 2159.83
   468.7 2165.74   473.1 2167.91   503.8  2171.6     538 2183.06     550 2187.94
   578.9 2195.06   616.2 2206.52     630 2209.25   685.4 2223.65   722.7 2231.26
#Mann= 3 ,-1,0
       0      .1       0  438.84    .045       0  456.81      .1       0
#XS Ineff= 2 , 0
          397.98 2185.55
Permanent Ineff=
       F       F
Bank Sta=438.84,456.81
XS Rating Curve= 0 ,0
Exp/Cntr(USF)=0,0
Exp/Cntr=0.3,0.1

Type RM Length L Ch R = 1 ,19946   ,145.6,144.3,142.4
XS GIS Cut Line= 4
2249431.01800863700965.2788378542249663.00504365701033.510318744
2249942.35275365701011.0340662152250151.06081284700922.734502711
#Sta/Elev= 30
       0 2195.77      28 2193.21    47.1 2190.24    87.8 2179.13   103.9 2176.68
   147.1 2171.79   163.8 2169.04   216.7 2166.85   230.5 2165.12     251 2158.67
  263.51 2150.78   271.1 2149.13   276.6 2150.78   279.1 2152.03   284.1 2152.76
   303.2 2151.83   339.3 2152.47   347.3 2153.35   359.4 2153.41   387.5 2155.07
   447.5 2153.78   467.7 2154.79   537.1 2161.22   571.8 2163.32   589.2 2166.41
   606.6 2170.52     650 2182.72   677.5 2189.01   723.8 2196.39   748.7 2198.37
#Mann= 3 ,-1,0
       0      .1       0  263.51    .045       0   276.6      .1       0
Bank Sta=263.51,276.6
XS Rating Curve= 0 ,0
Exp/Cntr(USF)=0,0
Exp/Cntr=0.3,0.1

Type RM Length L Ch R = 1 ,19801   ,45.2,44.7,45
XS GIS Cut Line= 6
2249415.74023758 700993.308892942249723.31396942701150.569806283
2249839.64781006701138.2837241032249912.21248294701162.088008327
2249991.02076425701236.6340145592250184.47202389701062.429321097
#Sta/Elev= 30
       0 2196.42    40.7 2194.23    68.9 2190.12   103.2 2178.18   121.1 2175.45
   170.6 2172.16   250.6 2164.63   342.9 2151.26   358.7 2147.88   378.8 2147.26
  387.682144.497     391 2143.97  398.042144.491   407.4 2146.05   420.1 2145.12
   460.5 2147.56   497.7 2145.73   514.5 2146.63   530.5 2144.04   621.9 2144.83
   649.2 2148.94   666.6 2147.99   683.1 2150.93   702.2  2151.9     750 2158.58
     780 2160.23   794.1 2163.55   839.7  2166.6   869.6 2166.56   909.5 2174.03
#Mann= 3 ,-1,0
       0      .1       0  387.68    .045       0  398.04      .1       0
#XS Ineff= 2 , 0
                          459.21         2158.11
Permanent Ineff=
       F       F
Bank Sta=387.68,398.04
XS Rating Curve= 0 ,0
Exp/Cntr=0.3,0.1

Type RM Length L Ch R = 1 ,19757   ,205.2,205.8,207.2
XS GIS Cut Line= 6
2249417.69948375701038.3715547962249725.27321558701195.632468139
2249841.60705623701183.346385959 2249914.1717291701207.150670183
2249992.98001041701281.6966764152250186.43127005701107.491982953
#Sta/Elev= 30
       0 2195.53    30.8 2193.08    51.9 2189.96    81.5 2180.96   102.4 2175.93
   117.3 2173.78   275.2 2159.43   297.5 2156.69   311.3  2152.3   347.3 2150.67
   372.8 2145.67   397.2 2145.39  404.162142.812   409.7 2141.72   416.7 2142.82
   434.4 2145.89   496.8 2143.69   512.4 2141.13   529.7 2140.79   548.5  2143.5
   605.7 2144.25   673.9 2146.94   685.8 2149.15   697.2 2149.03   745.3  2154.2
   787.5 2157.15   804.2 2160.03   835.3 2161.16   852.9 2165.11   909.5 2167.65
#Mann= 3 ,-1,0
       0      .1       0  404.16    .045       0   416.7      .1       0
#XS Ineff= 2 , 0
          392.71 2157.92  436.82         2161.04
Permanent Ineff=
       F       F
Bank Sta=404.16,416.7
XS Rating Curve= 0 ,0
Exp/Cntr=0.3,0.1

Type RM Length L Ch R = 1 ,19551   ,642.1,655.3,661.2
XS GIS Cut Line= 4
 2249478.5782697701198.2449658852249758.69515908701399.781021064
 2250012.4421991701368.5188475362250235.24747174701164.903509748
#Sta/Elev= 30
       0 2177.42    16.8 2173.56    43.4 2171.12    59.8 2167.67    89.2 2166.46
   139.9 2161.06   169.8 2156.62   215.3 2154.31     264 2148.11   289.8 2145.97
   302.6 2146.11   366.7  2138.5   382.8 2138.84   391.8 2137.65  408.62 2137.67
   439.3 2138.96   483.6  2135.6   519.9 2138.12   531.7 2140.25   560.2 2139.92
   584.4 2141.35   611.2 2144.87   670.9 2148.53   694.6 2151.92   752.1 2154.25
   771.7 2157.96   795.4  2160.5   815.3  2159.9     828 2162.18   902.6  2168.2
#Mann= 3 ,-1,0
       0      .1       0   391.8    .045       0  408.62      .1       0
#XS Ineff= 2 , 0
          382.37    2141
Permanent Ineff=
       F       F
Bank Sta=391.8,408.62
XS Rating Curve= 0 ,0
Exp/Cntr=0.3,0.1

Type RM Length L Ch R = 1 ,18896   ,535.2,531.9,518.9
XS GIS Cut Line= 4
2249433.57871826701321.4871191542249416.65124852701638.016720862
2249481.51519594701764.5938233092249850.11436403701910.562283588
#Sta/Elev= 30
       0 2166.49    59.8 2161.33    83.8 2156.36   111.9 2152.14   131.9 2147.36
   151.9 2141.14   164.5 2135.02   171.9 2133.19     196 2135.07     236 2133.64
   374.5 2126.99     379 2126.63  387.512123.965   396.2 2123.05  405.372123.964
     426 2128.09   456.3 2127.86   470.7 2128.91   479.3  2128.2   535.7 2133.09
   556.7 2136.25   565.3 2135.26   595.4  2136.9     617 2140.55   655.2 2148.94
   681.5 2153.28   754.5 2160.16     773 2164.33   793.3 2170.36   855.7    2185
#Mann= 3 ,-1,0
       0      .1       0  387.51    .045       0  405.37      .1       0
Bank Sta=387.51,405.37
XS Rating Curve= 0 ,0
Exp/Cntr=0.3,0.1

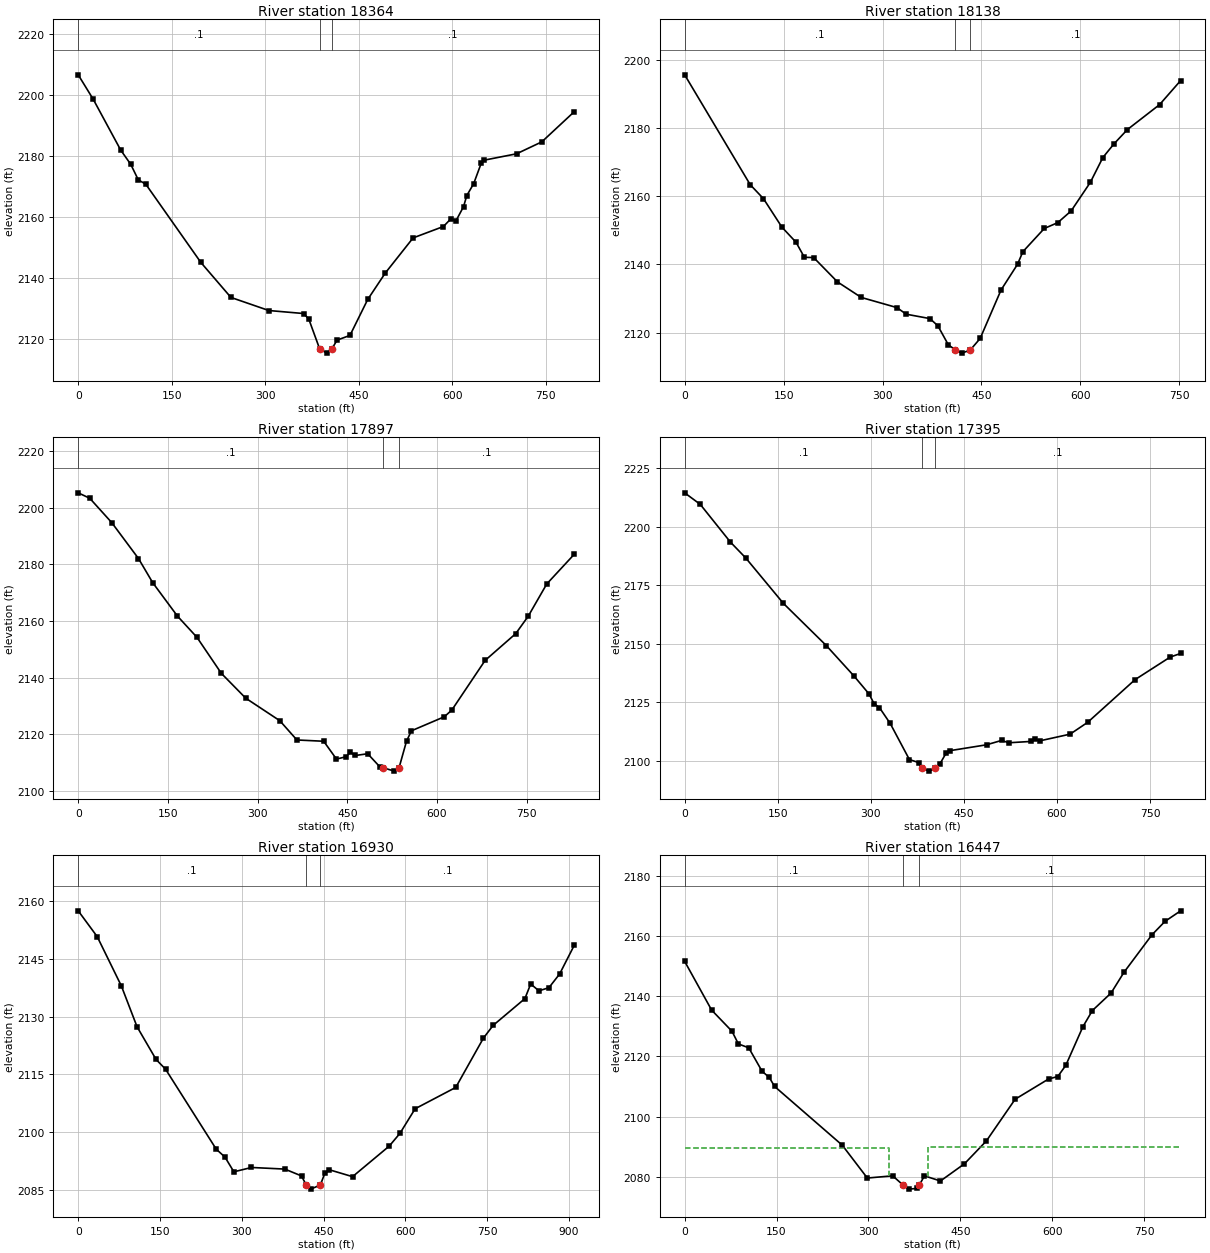
Type RM Length L Ch R = 1 ,18364   ,226.2,225.1,221.2
XS GIS Cut Line= 4
2249016.21568987701965.6430927082249362.91404733701997.717229955
2249455.68457347702020.7249667672249803.48711108702074.384392261
#Sta/Elev= 30
       0  2206.5    24.1 2198.49    68.2 2181.85    84.3 2177.19    96.4  2172.1
   108.4 2170.69   196.8 2145.06     245 2133.61   305.9 2129.32     362 2128.33
   370.1 2126.43  387.482116.702   398.9 2115.37  406.742116.702   415.4 2119.64
     436 2121.17   464.5 2132.95   492.8 2141.63   537.3  2153.1   585.9 2156.83
   598.1 2159.38   606.1  2158.7   618.3 2163.37   623.4 2166.95   634.5 2170.86
   646.6 2177.56   650.7 2178.53   703.3 2180.64   743.8 2184.55   795.7  2194.4
#Mann= 3 ,-1,0
       0      .1       0  387.48    .045       0  406.74      .1       0
Bank Sta=387.48,406.74
XS Rating Curve= 0 ,0
Exp/Cntr=0.3,0.1

Type RM Length L Ch R = 1 ,18138   ,241.9,241.6,239.3
XS GIS Cut Line= 4
2249040.91270555702208.5471351072249361.30086128702227.283284565
2249501.82198222702219.7888247812249787.54826145702168.264413772
#Sta/Elev= 30
       0 2195.56    99.4 2163.36   119.5 2159.26   147.5 2150.91   168.8 2146.51
   181.5 2142.09   195.6 2142.01   231.7 2134.88   267.7 2130.33   321.9 2127.35
   335.8 2125.42   371.9 2124.13   383.9 2122.02   399.9 2116.41   410.52114.972
     420 2114.01   432.82114.873     448  2118.3   479.7 2132.51   504.7 2140.04
   512.8 2143.73   545.3 2150.54   565.7 2152.24     586 2155.68   615.1 2164.05
   634.1 2171.33     651 2175.34   671.3 2179.52   720.1 2186.83     752 2193.87
#Mann= 3 ,-1,0
       0      .1       0   410.5    .045       0   432.8      .1       0
Bank Sta=410.5,432.8
XS Rating Curve= 0 ,0
Exp/Cntr(USF)=0,0
Exp/Cntr=0.3,0.1

Type RM Length L Ch R = 1 ,17897   ,504.7,502.2,497.7
XS GIS Cut Line= 4
     2249017.195      702370.0722249458.17535624702455.581805553
2249573.80494148702433.1162573712249819.76692428702341.816611915
#Sta/Elev= 30
       0 2205.19    19.3 2203.27      56  2194.7   100.8    2182   124.6 2173.48
     166 2161.68   198.6  2154.2   239.4 2141.48   280.1 2132.74   337.1 2124.79
   365.7 2117.99   410.5 2117.54   431.8 2111.26   447.2 2112.03   455.3 2113.63
   463.5 2112.52   484.1 2113.13   504.2 2108.55  510.362108.156   528.7    2107
  536.462108.156     549 2117.58   557.2 2121.23   612.2 2126.18   624.8 2128.56
   680.4 2146.06   731.6 2155.51   752.4 2161.62   783.5 2173.04   829.3 2183.47
#Mann= 3 ,-1,0
       0      .1       0  510.36    .045       0  536.46      .1       0
Bank Sta=510.36,536.46
XS Rating Curve= 0 ,0
Exp/Cntr=0.3,0.1

Type RM Length L Ch R = 1 ,17395   ,459.1,464.9,467.5
XS GIS Cut Line= 4
2249147.46953448 702931.640655252249504.92754009702869.363279231
2249571.94367292702821.065427525 2249830.8800518702580.224000042
#Sta/Elev= 30
       0 2214.59    25.1 2209.65    73.8 2193.49    98.2 2186.79   159.1  2167.3
   228.1 2149.29   272.8 2136.25   297.1 2128.56   305.2 2124.41   313.9  2122.7
   331.2 2115.94   362.1 2100.52   376.8 2099.25  383.172096.764     394 2095.57
  403.882096.766   411.2 2098.66   421.1  2103.2   428.3 2104.36   486.4 2106.83
   510.6  2108.7   522.2  2107.7   558.7 2108.28   564.4 2109.13   572.9 2108.56
     621 2111.38   649.3 2116.43   725.7  2134.7   782.3 2144.35   799.1 2145.89
#Mann= 3 ,-1,0
       0      .1       0  383.17    .045       0  403.88      .1       0
Bank Sta=383.17,403.88
XS Rating Curve= 0 ,0
Exp/Cntr=0.3,0.1

Type RM Length L Ch R = 1 ,16930   ,493.7,482.8,472.8
XS GIS Cut Line= 4
2249397.78192001703157.614131962 2249748.4269098703208.718965108
 2249901.3608566703153.173667637     2250158.548      702857.019
#Sta/Elev= 30
       0 2157.49    34.8 2150.79    79.1 2137.97   107.9 2127.34   142.8 2118.84
   160.1 2116.33     253 2095.54   269.2 2093.44   285.4 2089.64   317.7 2090.77
   378.8 2090.35   409.4 2088.57  418.022086.218   426.4 2085.14  443.992086.219
     452 2089.21   460.5 2090.17     503 2088.38   570.2 2096.32   589.9 2099.64
   617.7 2106.03   692.2 2111.58     743 2124.41   760.7  2127.7     819 2134.67
   829.6 2138.47   844.7  2136.7     863  2137.5   882.6 2141.06   909.3 2148.48
#Mann= 3 ,-1,0
       0      .1       0  418.02    .045       0  443.99      .1       0
Bank Sta=418.02,443.99
XS Rating Curve= 0 ,0
Exp/Cntr=0.3,0.1

Type RM Length L Ch R = 1 ,16447   ,539.6,543.7,545.3
XS GIS Cut Line= 4
2250075.29357472703752.6219540642250145.48728417703428.573541367
2250170.73430996703367.4467021052250333.29142415 702988.90367357
#Sta/Elev= 30
       0 2151.64      44 2135.43    77.2 2128.39    87.7 2124.16   104.6 2122.87
   126.3 2115.08   138.2 2112.99   146.8 2110.01   257.3 2090.45   298.2 2079.52
   339.6 2080.26  356.292077.235   365.5 2075.83   378.5 2076.04  383.182077.237
   391.5 2080.25   417.6 2078.54   456.8 2084.27   492.6 2091.88   539.5 2105.75
     594 2112.48   609.1 2113.31   622.2 2117.01   650.2 2129.91   665.7 2135.29
   696.2 2141.12   717.2    2148   762.9 2160.48   784.2 2164.96   809.7 2168.47
#Mann= 3 ,-1,0
       0      .1       0  356.29    .045       0  383.18      .1       0
#XS Ineff= 2 , 0
          334.37 2089.67  396.98         2089.86
Permanent Ineff=
       F       F
Bank Sta=356.29,383.18
XS Rating Curve= 0 ,0
Exp/Cntr=0.3,0.1

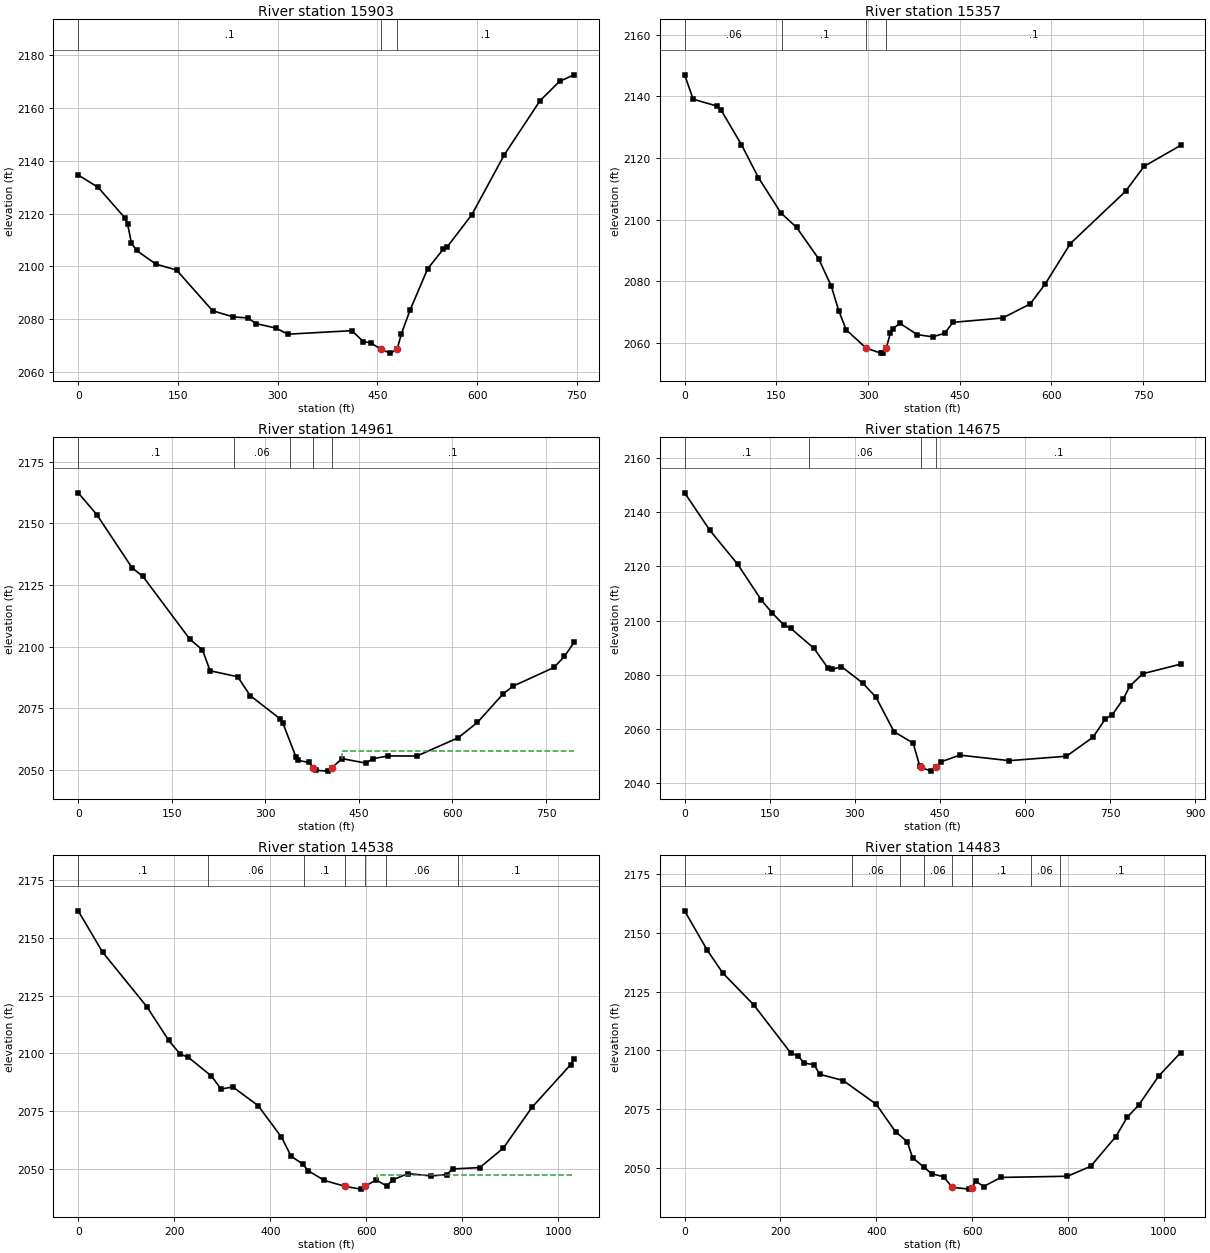
Type RM Length L Ch R = 1 ,15903   ,529.5,545.8,552.2
XS GIS Cut Line= 4
2250353.60038579703815.5412841712250616.96748606703522.090991008
2250689.71003364 703421.377541672250820.35213109703235.288746505
#Sta/Elev= 30
       0 2134.63      30 2129.92    69.7 2118.48    74.3 2115.98      80 2108.81
    87.7 2105.99   116.8 2100.79     148 2098.54     202 2083.11   232.9 2080.77
   255.4 2080.36   267.4 2078.22   297.3 2076.53   315.3  2074.2   411.6 2075.53
   428.8 2071.42   440.8 2070.85  455.262068.423   469.4 2067.01  479.582068.422
   486.1 2074.32     499 2083.25   525.6    2099   549.2  2106.5   554.9  2107.3
   592.1 2119.56     641 2142.33   694.7 2162.84     724 2170.15   745.9 2172.64
#Mann= 3 ,-1,0
       0      .1       0  455.26    .045       0  479.58      .1       0
Bank Sta=455.26,479.58
XS Rating Curve= 0 ,0
Exp/Cntr=0.3,0.1

Type RM Length L Ch R = 1 ,15357   ,406.2,396.2,390.2
XS GIS Cut Line= 4
2250386.48521743703938.7491787312250649.55122801703878.888607739
2250766.59543741703873.9502131142251179.48285217703776.800228007
#Sta/Elev= 30
       0 2146.98      14 2139.06    52.9 2136.84    59.5 2135.61      93 2124.28
   120.7 2113.62   157.6 2102.13   183.2 2097.44   219.2 2087.27   239.7  2078.5
     252 2070.46   264.3  2064.2  296.77 2058.31   320.5 2056.64   324.5 2056.67
  329.79 2058.31   336.5 2063.12   340.5 2064.63   352.5 2066.28   380.5 2062.64
   405.5 2061.94   425.5 2063.09   438.8 2066.63   520.1 2068.04   565.3 2072.61
   589.9 2079.11     631 2092.22   721.4 2109.21   751.5 2117.27   811.1 2124.05
#Mann= 4 ,-1,0
       0     .06       0     160      .1       0  296.77    .045       0
  329.79      .1       0
Bank Sta=296.77,329.79
XS Rating Curve= 0 ,0
Exp/Cntr=0.3,0.1

Type RM Length L Ch R = 1 ,14961   ,287.5,285.9,281.3
XS GIS Cut Line= 4
2250498.50816945704279.1838792922250839.87793143704236.879757309
2250931.41693606704183.3713052392251201.46923846703968.649241295
#Sta/Elev= 30
       0 2162.37    29.9  2153.5    86.3    2132   103.7  2128.5     179 2103.03
   199.2 2098.72   211.4 2090.25   255.6 2087.82   275.8 2080.17   324.1 2070.68
   328.2 2068.99     349 2055.36   352.8 2053.91   370.3 2053.07  376.82 2051.02
     382 2049.89   399.9 2049.57   406.8 2051.01   423.1 2054.63   461.2 2052.81
     472 2054.58     497 2055.73     543 2055.69   609.4 2063.13   640.1 2069.33
   680.9 2080.79   696.9 2083.98   762.7 2091.58   779.5 2096.05     795 2101.79
#Mann= 5 ,-1,0
       0      .1       0     250     .06       0     340      .1       0
  376.82    .045       0   406.8      .1       0
#XS Ineff= 2 , 0
                          423.09         2057.83
Permanent Ineff=
       F       F
Bank Sta=376.82,406.8
XS Rating Curve= 0 ,0
Exp/Cntr=0.3,0.1

Type RM Length L Ch R = 1 ,14675   ,116.1,137.3,148.6
XS GIS Cut Line= 3
2250620.18207248704538.6315357372251014.57801858704466.497360323
2251361.19678356704144.235589642
#Sta/Elev= 30
       0 2147.11    44.7 2133.24    93.5  2120.8   135.3 2107.58   154.5  2102.8
   174.8 2098.42   186.9  2097.2   228.1 2089.78   252.1 2082.73   260.2 2082.05
   276.5 2083.07   314.1 2076.99   337.5 2071.74   369.1 2059.11   402.9 2054.86
   414.3 2046.56  416.36    2046   434.1 2044.55     444 2046.04   452.3 2048.01
   485.1 2050.44   572.4 2048.41   673.1 2050.04     720 2057.06   741.7 2063.79
     754 2065.36     773 2071.02   784.7 2075.84   807.7 2080.45   874.2 2083.96
#Mann= 4 ,-1,0
       0      .1       0     220     .06       0  416.36    .045       0
     444      .1       0
Bank Sta=416.36,444
XS Rating Curve= 0 ,0
Exp/Cntr(USF)=0,0
Exp/Cntr=0.3,0.1

Type RM Length L Ch R = 1 ,14538   ,44.6,54.6,51.6
XS GIS Cut Line= 6
2250578.23708755704560.9377853772251048.08102557704486.169618701
 2251108.3245635704532.3952370652251168.27463207704545.678540802
2251251.26621783704499.2217925582251570.99573969704459.351656983
#Sta/Elev= 30
       0 2161.64    50.6 2143.82   143.7 2119.95   188.3  2105.6   212.6 2099.58
   228.8 2098.34   277.4 2090.15   297.6 2084.53   321.9 2085.45   374.6 2077.35
   423.2 2063.74   443.4 2055.44   467.8 2052.08     478 2049.29   512.6    2045
   556.2 2042.41   588.6 2041.24   596.1  2042.4   620.4 2045.17     642 2042.67
   655.3 2045.27   686.6 2047.97   735.4 2046.95   767.6 2047.55   779.7 2049.97
   836.2 2050.56     885 2058.96     945 2076.68  1025.6 2095.15  1032.5 2097.75
#Mann= 7 ,-1,0
       0      .1       0     270     .06       0     470      .1       0
   556.2    .045       0   596.1      .1       0  641.33     .06       0
   790.3      .1       0
#XS Ineff= 2 , 0
                          621.39         2047.18
Permanent Ineff=
       F       F
Bank Sta=556.2,596.1
XS Rating Curve= 0 ,0
Exp/Cntr(USF)=0,0
Exp/Cntr=0.3,0.1

Type RM Length L Ch R = 1 ,14483   ,245.9,227.1,222.9
XS GIS Cut Line= 6
2250589.43277994704602.2996489162251059.27671796 704527.53148224
2251171.39592786 704593.14479577 2251220.6124428704573.602501957
2251262.46191022704540.5836560982251582.19143208704500.713520523
#Sta/Elev= 30
       0 2159.38    47.3 2142.59    79.7 2132.89   144.5 2119.26   221.5 2098.82
   236.2 2097.63   249.8 2094.51   270.1 2093.82   282.2 2089.72   330.9 2087.08
   399.7 2077.02   440.2 2065.27   464.5 2061.06   475.8 2054.23     500 2050.07
   515.6 2047.36   540.8 2046.08   558.22041.586   594.1  2040.8   599.8 2041.45
   607.5 2044.26     624 2041.91   660.2 2045.79   799.2 2046.29   847.6 2050.52
     900 2063.18   924.2 2071.51   948.4 2076.75   989.8 2089.06  1035.1 2098.87
#Mann= 8 ,-1,0
       0      .1       0     350     .06       0     450      .1       0
     500     .06       0   558.2    .045       0   599.8      .1       0
  722.86     .06       0  782.86      .1       0
Bank Sta=558.2,599.8
XS Rating Curve= 0 ,0
Exp/Cntr=0.3,0.1

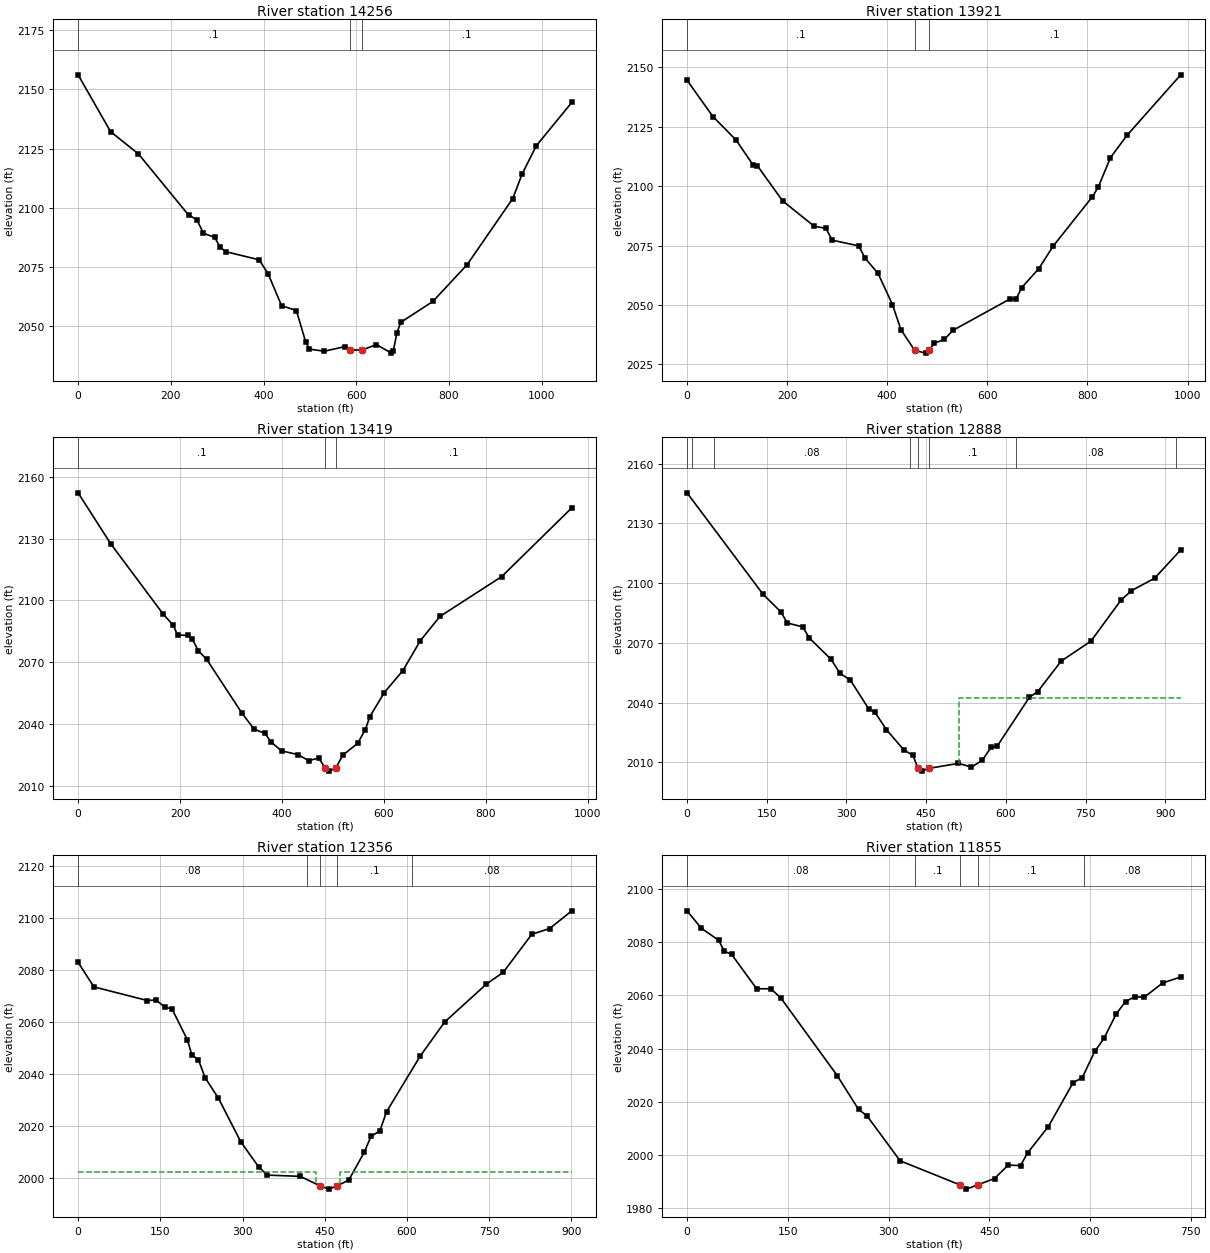
Type RM Length L Ch R = 1 ,14256   ,330.9,335.7,340.5
XS GIS Cut Line= 4
 2250622.1864394704758.2120474992251177.15563763704793.888638814
2251319.86200289704777.0413595822251676.62791604 704855.33165719
#Sta/Elev= 30
       0 2156.19    70.1 2132.14   130.3  2122.7   238.2 2096.86     256 2094.95
   270.5 2089.12   294.6 2087.44   306.6 2083.25   318.6 2081.36   390.8  2077.9
   410.2 2071.87   438.9 2058.54     471 2056.42     491 2043.14     499 2040.12
   531.1 2039.22   575.3 2041.17   586.2 2039.75  612.492039.715   643.7 2042.04
     676 2038.42     680 2039.39     688  2047.1   696.1 2051.46   765.7 2060.34
   839.4 2075.89   937.7 2103.82   958.1  2114.3   988.6 2126.19  1065.1 2144.52
#Mann= 3 ,-1,0
       0      .1       0   586.2    .045       0  612.49      .1       0
Bank Sta=586.2,612.49
XS Rating Curve= 0 ,0
Exp/Cntr(USF)=0,0
Exp/Cntr=0.3,0.1

Type RM Length L Ch R = 1 ,13921   ,503.9,501.1,498.6
XS GIS Cut Line= 4
2250639.16879839 704886.65295339 2251052.2394191 705025.75777923
2251137.90650778 705048.083269152251589.31497595705146.477210285
#Sta/Elev= 30
       0 2144.63    51.7 2129.35    98.1 2119.43   131.9 2108.99   140.3  2108.7
     191 2093.83   254.3 2083.13   277.5 2082.29   290.1 2077.29   342.9  2074.9
   355.6 2069.77   381.7 2063.29   410.5 2050.15   427.4 2039.59  454.842030.909
   477.1 2029.74  483.89 2030.91   493.7 2033.93     514 2035.48   531.2 2039.32
   645.4 2052.56   657.7 2052.54   668.4 2057.25   702.8 2065.31   731.4 2074.76
   809.6  2095.5   821.5 2099.57     846 2112.05   878.8 2121.39   986.4 2146.91
#Mann= 3 ,-1,0
       0      .1       0  454.84    .045       0  483.89      .1       0
Bank Sta=454.84,483.89
XS Rating Curve= 0 ,0
Exp/Cntr=0.3,0.1

Type RM Length L Ch R = 1 ,13419   ,531.3,531.7,534
XS GIS Cut Line= 4
2250573.39255174705433.9982241532250992.13837934705523.217224153
2251113.40505217705532.180923485 2251528.4271724705590.640724174
#Sta/Elev= 30
       0 2152.26    64.2 2127.47   166.4 2093.57   186.9 2087.91   195.1 2083.24
   215.5 2083.06   223.7 2081.47     236 2075.56   252.3 2071.45   321.8 2045.23
   345.5 2037.54   366.8 2035.47   379.1  2031.2   399.6 2026.99   432.2 2025.17
   452.2 2022.25   472.3 2023.53  485.182018.589   492.4 2017.18  505.562018.589
   519.6 2024.99   548.5  2030.6   563.7 2037.38   572.7 2043.69     601 2055.34
   637.4    2066   671.6 2080.47   710.1 2092.26   831.3  2111.6   968.9 2144.97
#Mann= 3 ,-1,0
       0      .1       0  485.18    .045       0  505.56      .1       0
Bank Sta=485.18,505.56
XS Rating Curve= 0 ,0
Exp/Cntr=0.3,0.1

Type RM Length L Ch R = 1 ,12888   ,533.8,531.8,528.2
XS GIS Cut Line= 4
2250433.99233948705905.948660521 2250839.3765045706016.357522932
2250985.49969177706047.1902569852251345.12172482706055.635798111
#Sta/Elev= 30
       0 2145.39   143.2 2094.39   176.4 2085.66   188.8 2080.01   217.8 2078.05
   230.3 2072.42   271.1 2061.78   287.9 2054.71   307.4 2051.33   342.2 2036.78
     353 2035.43   375.4 2026.41   408.4 2016.16   425.1 2013.61  434.732007.016
   441.4 2005.62   455.3 2007.01   510.9 2009.51   535.4 2007.66   555.9 2011.13
   572.2 2017.56   584.2 2018.34   644.4 2042.72   660.1 2045.59   704.2 2060.88
   760.2 2070.91   816.4 2091.36   836.2  2096.2   880.3 2102.55   929.2 2116.73
#Mann= 8 ,-1,0
       0     .08       0      10      .1       0      50     .08       0
     420      .1       0  434.73    .045       0   455.3      .1       0
  619.49     .08       0  919.49      .1       0
#XS Ineff= 2 , 0
                          512.64         2042.37
Permanent Ineff=
       F       F
Bank Sta=434.73,455.3
XS Rating Curve= 0 ,0
Exp/Cntr=0.3,0.1

Type RM Length L Ch R = 1 ,12356   ,507.5,500.5,489.3
XS GIS Cut Line= 4
     2250431.837       706499.53  2250753.944799706555.453771993
2250936.37902268706540.9567457512251319.82716476706466.193854431
#Sta/Elev= 30
       0 2083.05    28.8  2073.6   126.3 2068.34   142.4 2068.55   158.7 2065.66
   170.9 2065.27   199.3 2053.24   207.4  2047.5   219.6 2045.44   231.8 2038.59
   256.1 2030.68   296.7 2013.96   329.2 2004.33   345.2 2001.12   405.4 2000.63
   441.8 1996.93   457.5 1995.72  472.071996.931   493.7 1999.21     522 2009.92
   534.2    2016   550.5 2018.18   562.7 2025.53   623.8 2046.86   668.7 2060.07
   744.9 2074.68   775.6 2079.22   827.6 2093.84   860.2 2096.07   900.6 2102.88
#Mann= 5 ,-1,0
       0     .08       0  416.93      .1       0   441.8    .045       0
  472.07      .1       0  609.94     .08       0
#XS Ineff= 2 , 0
          433.44 2002.19  477.84         2002.15
Permanent Ineff=
       F       F
Bank Sta=441.8,472.07
XS Rating Curve= 0 ,0
Exp/Cntr=0.3,0.1

Type RM Length L Ch R = 1 ,11855   ,142.5,145,147.9
XS GIS Cut Line= 4
2250658.98489381707244.622066241 2250956.7272535707029.715271689
2251034.18810508706960.2511195692251263.67435847706830.170220444
#Sta/Elev= 30
       0 2091.81    21.2 2085.29    46.9 2080.77    55.7 2076.62    66.4 2075.43
   103.6 2062.53   124.8 2062.49   139.6 2059.07   223.5 2029.91   255.4 2017.14
   267.9 2014.76   317.2 1997.86  405.72 1988.85   415.9  1987.2   433.9 1988.91
   457.8 1991.18   478.1 1996.22   496.5 1996.06   507.2 2000.89   537.9  2010.7
   574.7 2027.19   588.5 2029.13     607 2038.97   620.7 2043.84   639.1 2053.12
   652.8  2057.7   666.6 2059.55   680.4 2059.29     708 2064.68     735 2066.94
#Mann= 5 ,-1,0
       0     .08       0     340      .1       0  405.72    .045       0
   433.9      .1       0  591.24     .08       0
Bank Sta=405.72,433.9
XS Rating Curve= 0 ,0
Exp/Cntr=0.3,0.1