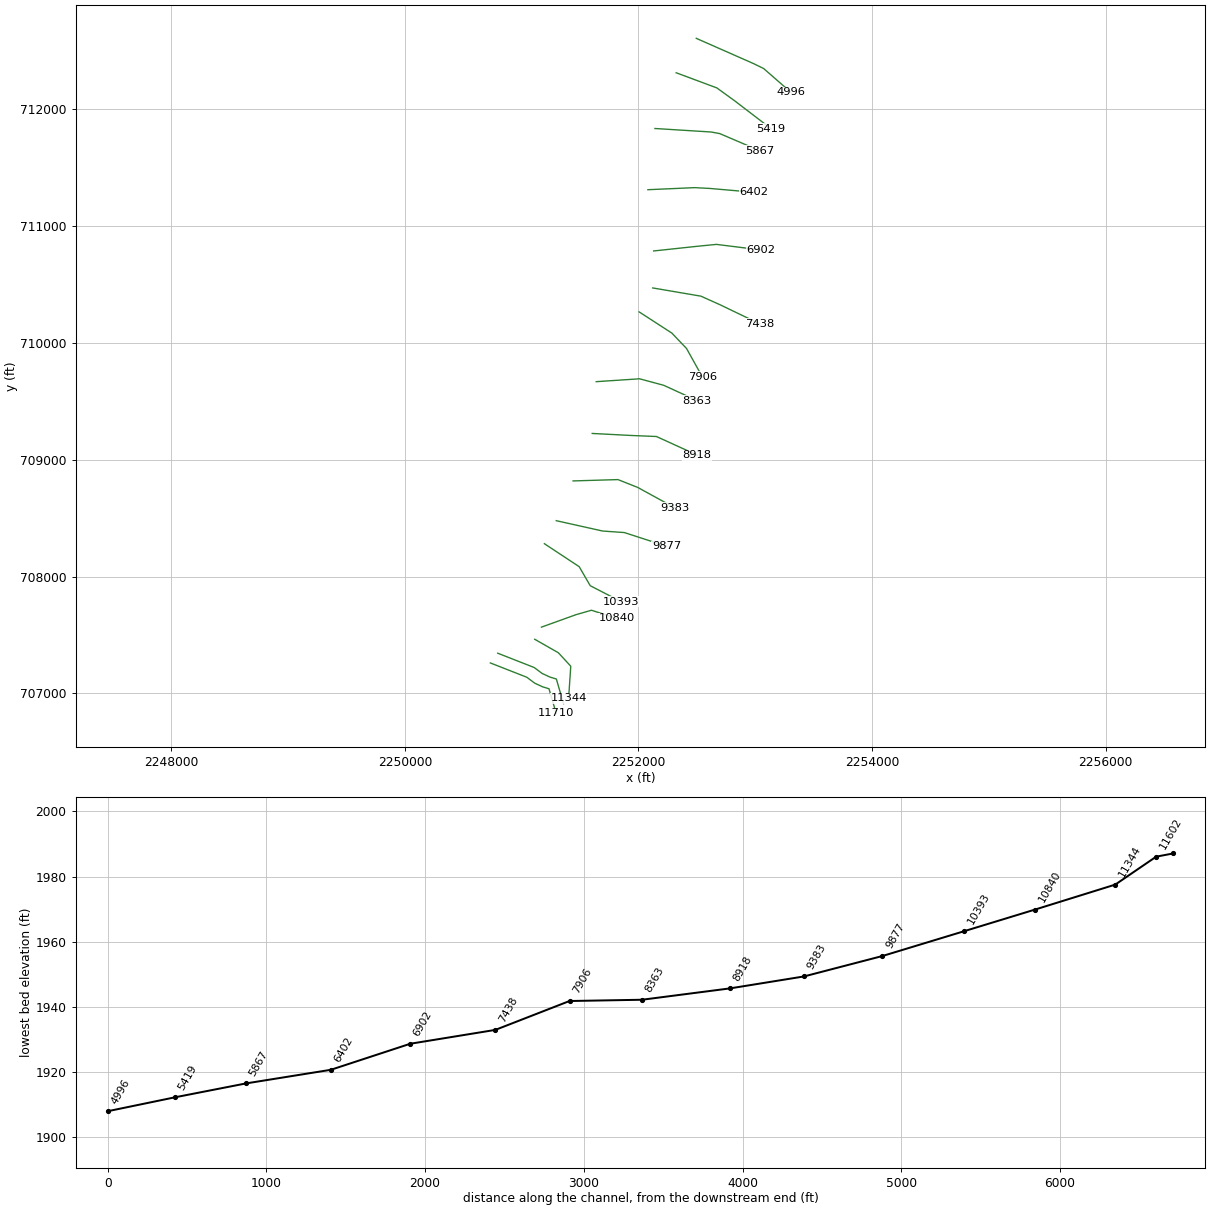
HEC-RAS study BIGLAURLRN.prj: BIGLAURLRN

--- BIGLAURLRN.g01 (geometry) --- (continued)

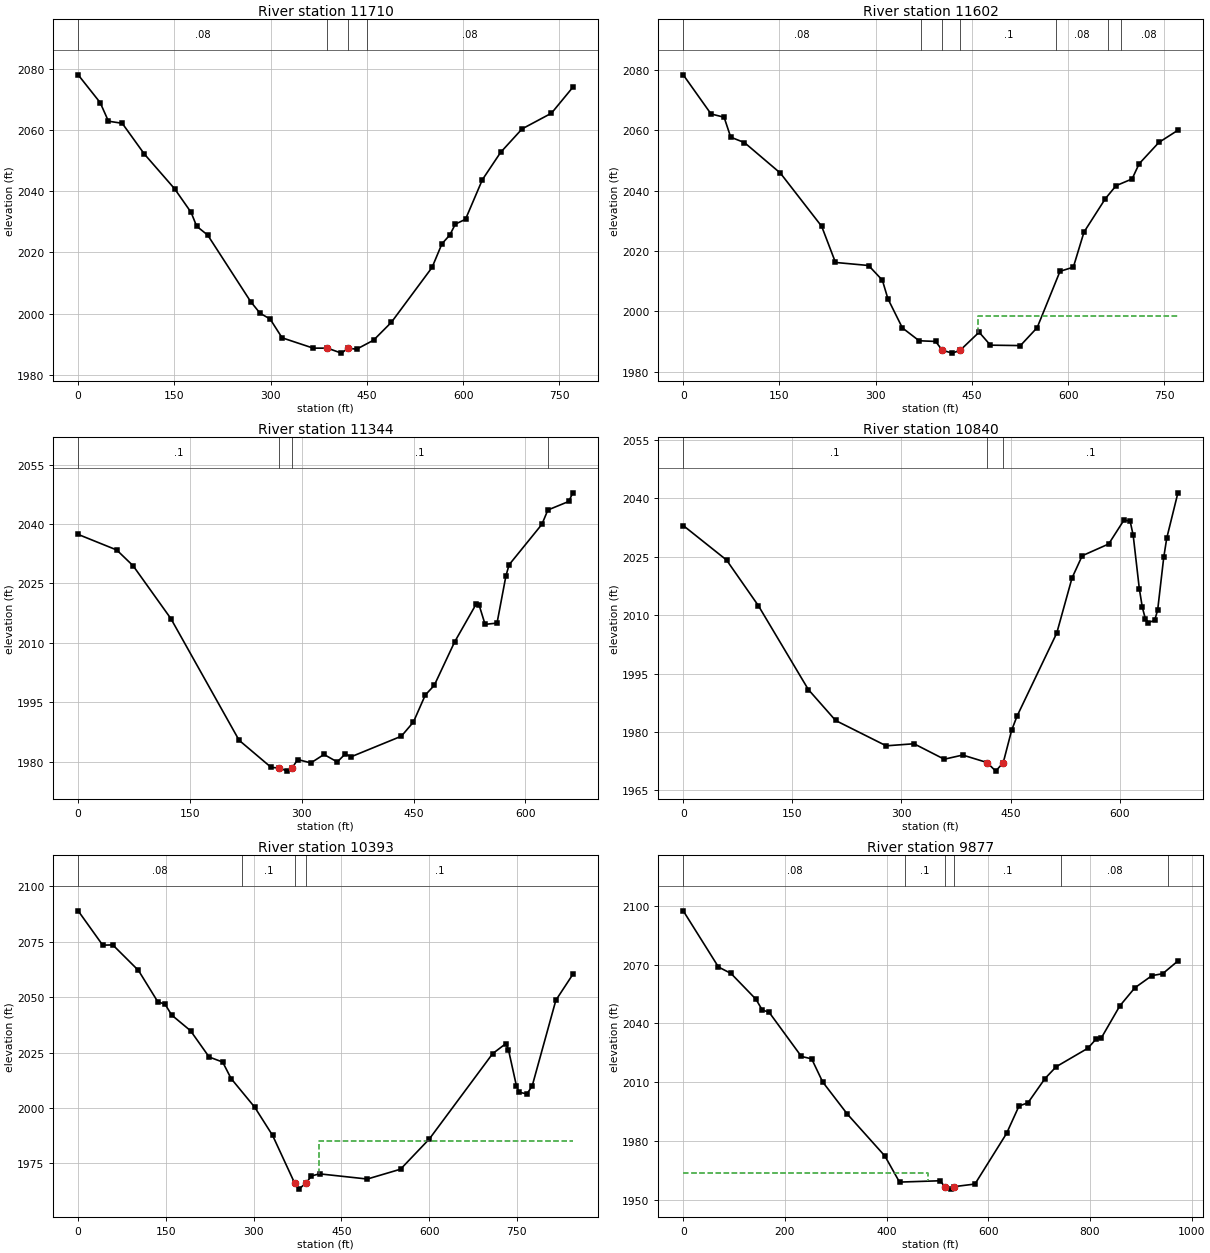
Type RM Length L Ch R = 1 ,11710   ,110,108.8,109.1
XS GIS Cut Line= 6
2250732.21226919707261.0133366882251044.57000025707138.401711628
2251111.95148221707087.9519866762251178.64187204707056.852841157
2251234.27478792707039.9210841522251295.52476877706829.224014914
#Sta/Elev= 30
       0 2077.96    34.3  2068.9    47.2 2062.83    68.7 2062.14   103.1 2052.13
   150.4 2040.76   176.1 2033.06   184.7 2028.55   201.9 2025.67     269 2003.93
   283.6 2000.15   299.2 1998.28   317.9 1992.14   366.4 1988.77  388.641988.762
   410.3 1987.14  420.961988.741     434 1988.42   460.4 1991.35   488.3 1997.21
   551.7 2015.11     567 2022.79   579.5 2025.73   587.9 2029.23   603.8 2030.82
   630.1 2043.74   658.6 2052.67     692 2060.32   737.8 2065.44   771.1  2073.9
#Mann= 4 ,-1,0
       0     .08       0  388.64    .045       0  420.96      .1       0
  449.87     .08       0
Bank Sta=388.64,420.96
XS Rating Curve= 0 ,0
Exp/Cntr(USF)=0,0
Exp/Cntr=0.3,0.1

Type RM Length L Ch R = 1 ,11602   ,259,257.8,249.7
XS GIS Cut Line= 6
2250795.25428038707344.4373514922251107.61201144707221.825726431
 2251174.9934934707171.3760014792251241.68388323 707140.27685596
 2251297.3167991707123.3450989562251358.56677995706912.648029718
#Sta/Elev= 30
       0 2078.37    43.3 2065.41    63.7 2064.32      74 2057.71    95.5  2055.9
   151.4  2045.8   215.8 2028.16   237.3 2016.19   288.9 2015.18   310.4 2010.32
     319 2004.18   341.6  1994.5   367.7 1990.24   393.4 1990.01  403.811987.092
   419.4 1986.14  431.731987.092   461.2 1993.08   478.8 1988.78   525.6 1988.64
   551.7 1994.59   587.3 2013.25   608.1 2014.63   624.7 2026.26   658.1 2037.36
   674.7 2041.63   699.7 2043.87   710.6 2048.88   741.4 2055.96   771.1 2060.01
#Mann= 7 ,-1,0
       0     .08       0  371.05      .1       0  403.81    .045       0
  431.73      .1       0  581.67     .08       0  661.67      .1       0
  681.67     .08       0
#XS Ineff= 2 , 0
                          459.79         1998.28
Permanent Ineff=
       F       F
Bank Sta=403.81,431.73
XS Rating Curve= 0 ,0
Exp/Cntr(USF)=0,0
Exp/Cntr=0.3,0.1

Type RM Length L Ch R = 1 ,11344   ,490.1,504.3,512.9
XS GIS Cut Line= 4
2251112.11046489707463.6831480932251314.80760455707347.978300864
2251420.68945277707233.0170621972251402.23563847706959.732209476
#Sta/Elev= 30
       0 2037.39    51.7 2033.46    73.8 2029.45   124.4 2016.11   215.9 1985.37
     259  1978.5   269.8 1978.37   280.7 1977.57  287.11  1978.4   294.5  1980.5
   312.2 1979.65   329.8 1981.78   347.6 1979.89   358.1 1981.87   366.6 1981.23
   433.6  1986.4   449.7 1989.96   465.7 1996.81   477.7 1999.24     505 2010.21
   533.9 2019.78   537.9 2019.52   545.9 2014.66   561.9 2014.98   573.9 2026.95
   578.1 2029.72   622.1 2039.94   630.1 2043.56   658.1 2045.72   663.6  2047.9
#Mann= 4 ,-1,0
       0      .1       0   269.8    .045       0  287.11      .1       0
  629.69     .08       0
Bank Sta=269.8,287.11
XS Rating Curve= 0 ,0
Exp/Cntr=0.3,0.1

Type RM Length L Ch R = 1 ,10840   ,456.3,446.8,430
XS GIS Cut Line= 4
2251169.58535088707567.6195109352251465.75686489  707674.3583603
2251597.83021711707712.2728605312251814.71351303707641.972064299
#Sta/Elev= 30
       0 2033.01    59.5 2024.16   103.3 2012.43     172 1990.89   209.5 1982.94
   279.1 1976.43   317.3 1976.96   358.9 1972.99   384.3 1974.06  417.791972.136
   429.7 1969.93  440.051972.138   451.6 1980.45   458.9 1984.01   513.6 2005.39
   534.6 2019.54   548.6 2025.25     585 2028.27   606.1 2034.43   614.5 2034.12
   618.7 2030.51   627.1 2016.82   631.3 2011.96   635.5 2009.04   639.7  2008.1
   648.1 2008.64   652.3 2011.23   660.7 2024.83   664.9 2029.82   680.2 2041.41
#Mann= 3 ,-1,0
       0      .1       0  417.79    .045       0  440.05      .1       0
Bank Sta=417.79,440.05
XS Rating Curve= 0 ,0
Exp/Cntr=0.3,0.1

Type RM Length L Ch R = 1 ,10393   ,506.3,515.5,525.1
XS GIS Cut Line= 4
2251194.80085443708282.0072184582251492.69385217708085.332295657
2251587.38515802707922.193023861 2251853.9958794707784.747017252
#Sta/Elev= 30
       0 2089.01      42 2073.49    59.2 2073.62   103.1 2062.07   135.9 2048.01
   148.8 2046.72   159.8 2041.94   192.1 2034.84   223.9 2022.97     247  2020.7
   261.4 2013.25   301.8 2000.28   332.4 1987.53  369.931966.055   377.2 1963.29
  389.581966.057   398.8 1969.25   412.6 1970.19   494.2 1967.85     551 1972.29
   600.4    1986   708.5 2024.51     731 2029.02   735.5 2026.23     749 2010.06
   753.5 2007.09     767 2006.29     776 2009.86   816.5 2048.62   845.5  2060.3
#Mann= 4 ,-1,0
       0     .08       0     280      .1       0  369.93    .045       0
  389.58      .1       0
#XS Ineff= 2 , 0
                          412.26         1985.11
Permanent Ineff=
       F       F
Bank Sta=369.93,389.58
XS Rating Curve= 0 ,0
Exp/Cntr=0.3,0.1

Type RM Length L Ch R = 1 ,9877    ,498.6,494.2,486.2
XS GIS Cut Line= 4
2251296.54693022708479.0164025612251693.84141704  708390.4193634
 2251879.5521658708377.331867071 2252240.7793183708260.116731069
#Sta/Elev= 30
       0 2097.35    69.3 2068.75    93.9 2065.48   143.1 2052.31   155.4 2046.87
   168.8 2045.74   232.4 2023.22   252.6    2022   274.2 2010.26   322.9 1993.83
   396.6 1972.54   425.4 1959.25   505.6 1959.93     5141956.953   525.7 1955.67
  533.351956.952   573.8 1958.26   635.9 1983.99   660.5 1998.02     678 1999.59
   711.6 2011.98   733.5 2017.97   795.7 2027.37   812.6 2032.21   822.4 2032.66
   858.8 2048.98   888.3 2058.16   921.9 2064.36   943.1 2065.35     973 2071.83
#Mann= 6 ,-1,0
       0     .08       0  437.05      .1       0     514    .045       0
  533.35      .1       0  743.22     .08       0  953.22      .1       0
#XS Ineff= 2 , 0
          481.79 1964.03
Permanent Ineff=
       F       F
Bank Sta=514,533.35
XS Rating Curve= 0 ,0
Exp/Cntr=0.3,0.1

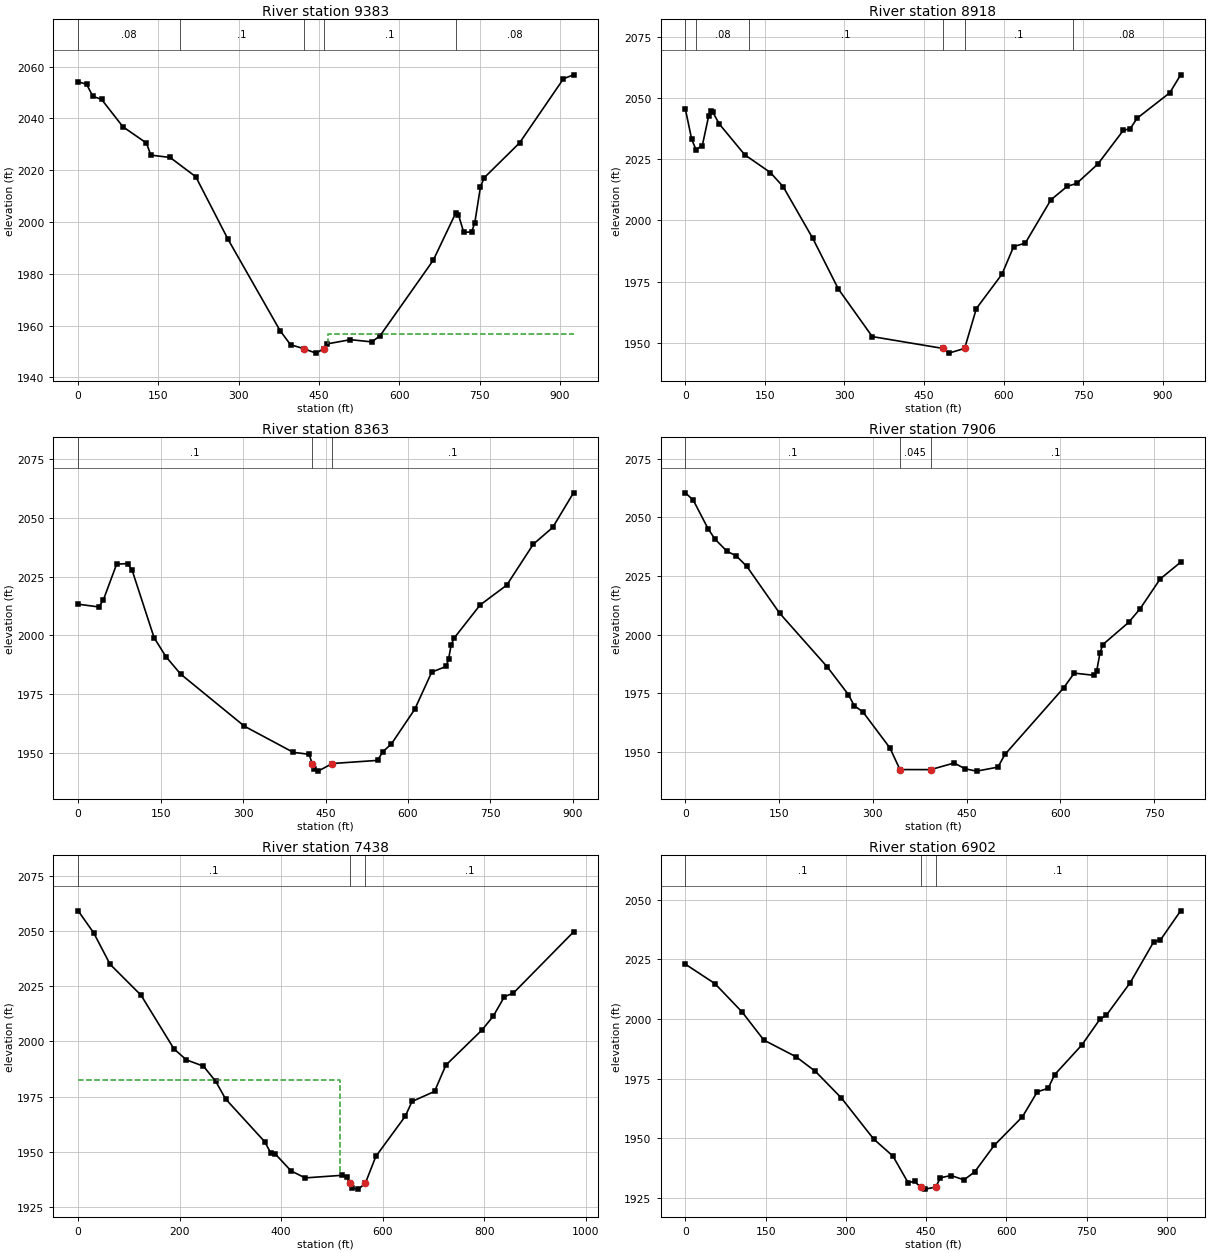
Type RM Length L Ch R = 1 ,9383    ,459.8,465.3,473
XS GIS Cut Line= 4
2251440.58945978708819.4478276872251824.98217564708830.866846966
 2251993.8440804708763.7330320282252308.56436015708591.279034504
#Sta/Elev= 30
       0 2054.18    15.6 2053.21    27.6 2048.52    43.6 2047.39    83.6 2036.79
   127.6  2030.5   135.6 2025.85   171.7 2024.95   219.7 2017.49   279.7 1993.41
   377.2 1958.05   396.6 1952.66  421.391951.114     444  1949.4  459.151951.116
   465.3 1952.97   508.4 1954.59   548.5 1953.74   563.9 1956.11   663.2 1985.25
   705.4 2003.57   710.3 2002.79   720.2 1996.01   734.9 1996.23   740.8 1999.72
   751.4 2013.63   758.5 2017.14   824.4 2030.56   906.5 2055.35   925.2 2056.85
#Mann= 5 ,-1,0
       0     .08       0     190      .1       0  421.39    .045       0
  459.15      .1       0  706.28     .08       0
#XS Ineff= 2 , 0
                          465.79         1956.96
Permanent Ineff=
       F       F
Bank Sta=421.39,459.15
XS Rating Curve= 0 ,0
Exp/Cntr=0.3,0.1

Type RM Length L Ch R = 1 ,8918    ,554.3,555.1,538.2
XS GIS Cut Line= 4
2251604.19657279709225.918120724 2251940.5542955709208.507080249
2252153.99979639709199.8269713822252502.56922686709040.684541535
#Sta/Elev= 30
       0 2045.55      12 2033.15      20 2028.96      32 2030.54      44 2042.64
      48 2044.76      52 2044.13    64.1 2039.36   112.1 2026.79   160.2 2019.56
   184.2 2013.83   240.3 1992.61   288.4 1971.96   352.4 1952.49  485.471947.666
   496.6 1945.74  526.431947.665   548.6 1963.97   596.8    1978   618.8 1989.26
   640.8 1990.72   689.1 2008.42   720.1 2013.94   737.5 2015.07   777.5 2023.01
   825.4 2036.74   838.6 2037.52   851.8 2041.78   913.2 2052.16   933.6 2059.48
#Mann= 6 ,-1,0
       0      .1       0      20     .08       0     120      .1       0
  485.47    .045       0  526.43      .1       0  730.43     .08       0
Bank Sta=485.47,526.43
XS Rating Curve= 0 ,0
Exp/Cntr=0.3,0.1

Type RM Length L Ch R = 1 ,8363    ,464.7,457,440.4
XS GIS Cut Line= 4
 2251638.4226817709669.2432238312252009.88741479709693.888446476
2252216.57800665 709638.174867642252502.62531421709507.092134137
#Sta/Elev= 30
       0  2013.3    37.8 2012.12    45.9 2015.19    69.9 2030.32    89.9 2030.59
      98 2027.84   138.1 1999.03   159.5    1991   186.2 1983.59   302.4 1961.37
   391.2 1950.25   420.2 1949.41  425.431945.493   428.5 1943.03   436.5 1942.25
  462.25 1945.49   544.5 1946.82   554.2 1950.54   569.4  1953.7   612.3  1968.6
   643.1  1984.4   669.5 1986.82   673.9 1990.12   678.3 1995.76   683.3 1998.71
   731.1 2012.96   779.5  2021.4   827.9 2038.84   863.1 2045.95     901  2060.7
#Mann= 3 ,-1,0
       0      .1       0  425.43    .045       0  462.25      .1       0
Bank Sta=425.43,462.25
XS Rating Curve= 0 ,0
Exp/Cntr=0.3,0.1

Type RM Length L Ch R = 1 ,7906    ,463,467.3,471.4
XS GIS Cut Line= 4
2252005.57482756710266.9588621082252286.42484397710085.069633094
2252411.90029041709953.1811708682252546.14387936709712.569948285
#Sta/Elev= 30
       0 2060.44    12.6 2057.37    36.5 2045.09    47.4 2040.72    66.8  2035.5
    81.3 2033.62    98.4 2029.07   150.8 2009.16   227.1 1986.24   260.8 1974.47
     270 1969.81   284.3    1967   327.2 1951.75  343.281942.526   392.4  1942.5
     430 1945.32   447.4 1942.85   465.9 1941.86   499.9 1943.56   511.2 1948.98
   605.1 1977.34     622 1983.62   654.1 1982.67     658 1984.61   663.2 1992.25
   667.8 1995.79     709 2005.24   727.3 2011.02   759.4 2023.72   792.2 2030.89
#Mann= 3 ,-1,0
       0      .1       0  343.28    .045       0   392.4      .1       0
Bank Sta=343.28,392.4
XS Rating Curve= 0 ,0
Exp/Cntr=0.3,0.1

Type RM Length L Ch R = 1 ,7438    ,529.1,536.1,544.8
XS GIS Cut Line= 4
2252122.13941896710471.8641465812252535.03047174710401.367882146
2252698.84792781710327.898621331 2253038.8666207710164.326850019
#Sta/Elev= 30
       0 2059.22    30.5 2049.23    62.9 2034.96   123.8 2020.95   188.7 1996.59
   213.1 1991.63   246.7 1988.77     271 1981.86   290.2 1973.95   367.3 1954.53
   379.4  1949.4   387.6  1949.1   419.3 1941.27   447.1 1938.09   519.7 1939.27
   529.7 1938.52  535.131935.572   538.5 1933.39   551.6    1933  565.51 1935.57
   586.3 1947.82   644.3 1966.05   657.6 1972.75     702 1977.32   724.3 1989.24
   795.2 2005.12   817.4 2011.37   839.6 2020.28   857.3 2021.93   975.7 2049.64
#Mann= 3 ,-1,0
       0      .1       0  535.13    .045       0  565.51      .1       0
#XS Ineff= 2 , 0
          515.52 1982.54
Permanent Ineff=
       F       F
Bank Sta=535.13,565.51
XS Rating Curve= 0 ,0
Exp/Cntr=0.3,0.1

Type RM Length L Ch R = 1 ,6902    ,502.8,500.3,496.2
XS GIS Cut Line= 4
     2252130.371      710788.4252252502.10800519 710828.25976335
  2252667.441639710844.7033519612253049.92136015710797.125364027
#Sta/Elev= 30
       0 2022.96    55.3 2014.81   106.4 2002.84   146.6 1991.18     207 1984.16
   243.2 1978.03   291.5 1966.93   351.8 1949.74     388 1942.55   416.1 1931.48
   428.2 1931.98  439.411929.633   448.3 1928.75  468.011929.631   476.4 1933.51
   496.5 1934.44   520.7 1932.63   540.8 1936.03     577 1947.05   629.9 1959.08
   657.6  1969.5   677.8 1970.96   689.9 1976.65     741 1989.16   774.5 1999.88
   786.6 2001.56     831 2015.16   875.3 2032.39   887.4 2033.02   925.4 2045.29
#Mann= 3 ,-1,0
       0      .1       0  439.41    .045       0  468.01      .1       0
Bank Sta=439.41,468.01
XS Rating Curve= 0 ,0
Exp/Cntr=0.3,0.1

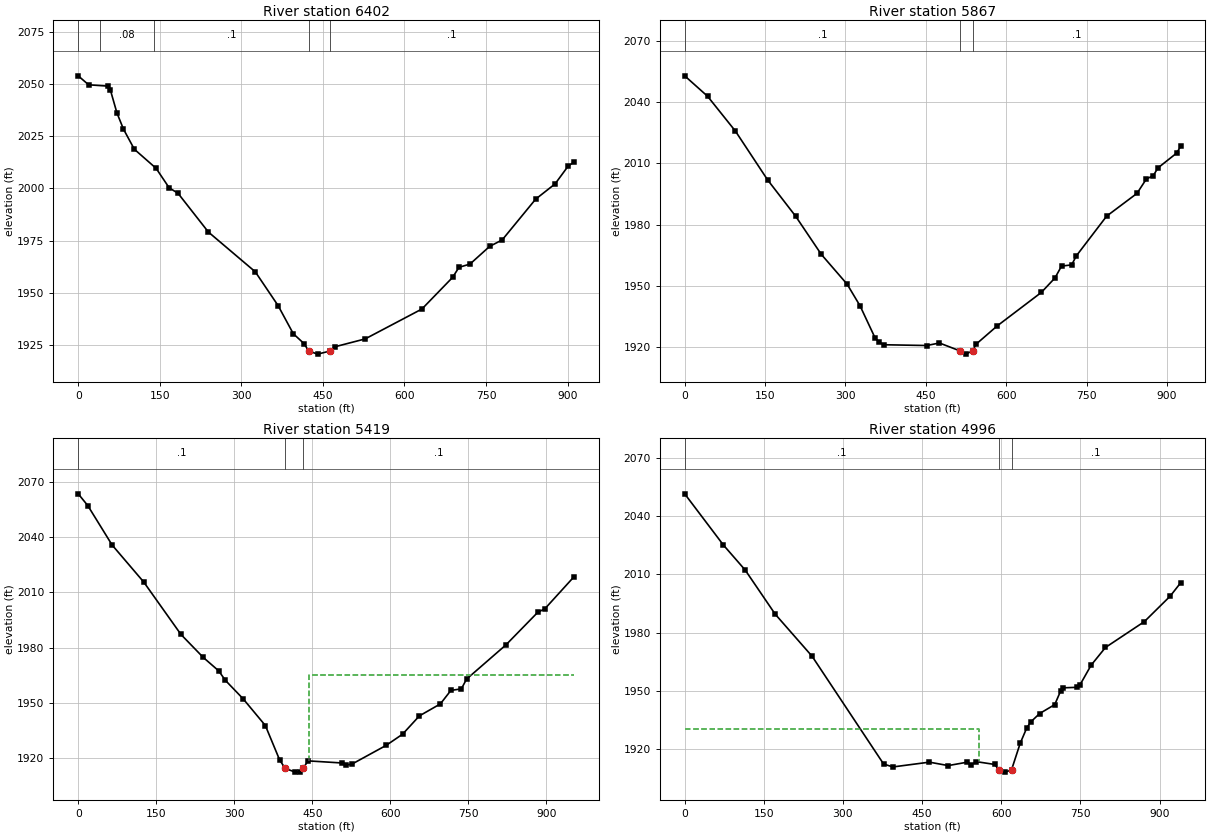
Type RM Length L Ch R = 1 ,6402    ,536.4,534.6,529.8
XS GIS Cut Line= 4
2252081.04918965711312.9094827692252481.56143105711330.618862066
2252611.14788755711323.6968704552252991.00418965711290.689224153
#Sta/Elev= 30
       0  2053.9    19.1 2049.61    55.2 2048.97    59.2 2047.09    71.2 2036.15
    83.2 2028.41   103.2 2018.78   143.3 2009.63   167.3 2000.31   183.5 1997.72
   239.4 1979.16   325.6 1960.15   367.5    1944   395.5 1930.53   415.5 1925.73
  423.791922.262   440.2 1920.76  463.48 1922.26   471.6 1924.25   527.7 1928.04
   632.1 1942.35   688.3 1957.43   700.3  1962.3   720.4 1963.83   756.5 1972.28
   779.7 1975.41   841.2  1994.9     877 2002.22   901.1 2010.76     912 2012.68
#Mann= 5 ,-1,0
       0      .1       0      40     .08       0     140      .1       0
  423.79    .045       0  463.48      .1       0
Bank Sta=423.79,463.48
XS Rating Curve= 0 ,0
Exp/Cntr=0.3,0.1

Type RM Length L Ch R = 1 ,5867    ,453.6,448.5,436.2
XS GIS Cut Line= 4
2252141.65002758711836.8725534572252622.26464155711806.994436451
2252695.87847087711793.5059160152253035.00821723711648.379315452
#Sta/Elev= 30
       0 2052.75    42.6 2042.78    94.7 2025.69   154.8  2001.8   206.9  1984.1
   254.9 1965.39   303.1 1950.79   327.2 1940.21   355.2 1924.53   363.2 1922.36
   371.2 1921.17   451.4 1920.79   475.4 1922.02  513.481918.178   524.2 1916.58
  537.441918.179   543.2 1921.32   582.8 1930.33   665.5 1946.78   690.9 1953.87
   703.1 1959.65     722 1960.24   730.7 1964.65   787.3  1984.1   843.9 1995.23
   861.3 2002.25   874.3 2003.92     883 2007.69   917.8 2014.92   925.3 2018.21
#Mann= 3 ,-1,0
       0      .1       0  513.48    .045       0  537.44      .1       0
Bank Sta=513.48,537.44
XS Rating Curve= 0 ,0
Exp/Cntr=0.3,0.1

Type RM Length L Ch R = 1 ,5419    ,422.4,422.9,420.7
XS GIS Cut Line= 4
 2252323.0529549712314.2048298072252671.53086043712184.366164254
2252823.87048482 712074.084212882253136.35048255711834.883447661
#Sta/Elev= 30
       0 2063.63    18.3 2057.27    65.2 2035.79   126.1 2015.62   197.6 1987.15
   240.2 1974.73   270.1 1967.38   282.9 1962.22   317.1 1952.17   359.8 1937.65
   387.5 1918.77  398.071914.338   417.1 1912.31     427 1912.53  432.451914.338
   441.8 1918.43   506.9 1917.29     515 1916.14   526.4 1916.69   592.2 1926.88
   623.6 1932.93     656  1942.9   696.3 1949.41   716.5 1956.74   736.6 1957.58
   746.7  1962.9   822.3 1981.48   883.2 1999.11   897.5 2001.22   953.5 2018.63
#Mann= 3 ,-1,0
       0      .1       0  398.07    .045       0  432.45      .1       0
#XS Ineff= 2 , 0
                          444.04         1965.24
Permanent Ineff=
       F       F
Bank Sta=398.07,432.45
XS Rating Curve= 0 ,0
Exp/Cntr=0.3,0.1

Type RM Length L Ch R = 1 ,4996    ,560.3,554.1,548.4
XS GIS Cut Line= 4
2252495.23642173712608.9139097482252985.10880107712392.857082186
2253072.44776823712350.1275265042253303.95313578712148.066443453
#Sta/Elev= 30
       0 2051.47    73.3 2025.11   114.7 2012.18   171.5 1989.47   241.5 1967.75
     377 1912.23   394.5 1910.72   463.8 1913.19   499.4 1911.42   534.4 1913.12
   543.4 1911.79   552.4 1913.46   587.8    1912  595.36 1909.17   607.5 1908.05
   619.41909.172   635.9 1922.94   648.2 1930.75   655.8  1933.9   672.8 1938.26
   701.3 1942.84   712.5 1949.86   717.2 1951.49   743.7 1951.76   749.1 1952.96
   770.3 1963.17   797.5  1972.3   871.2 1985.62     920 1998.71   939.9 2005.59
#Mann= 3 ,-1,0
       0      .1       0  595.36    .045       0   619.4      .1       0
#XS Ineff= 2 , 0
          557.02 1930.17
Permanent Ineff=
       F       F
Bank Sta=595.36,619.4
XS Rating Curve= 0 ,0
Exp/Cntr=0.3,0.1