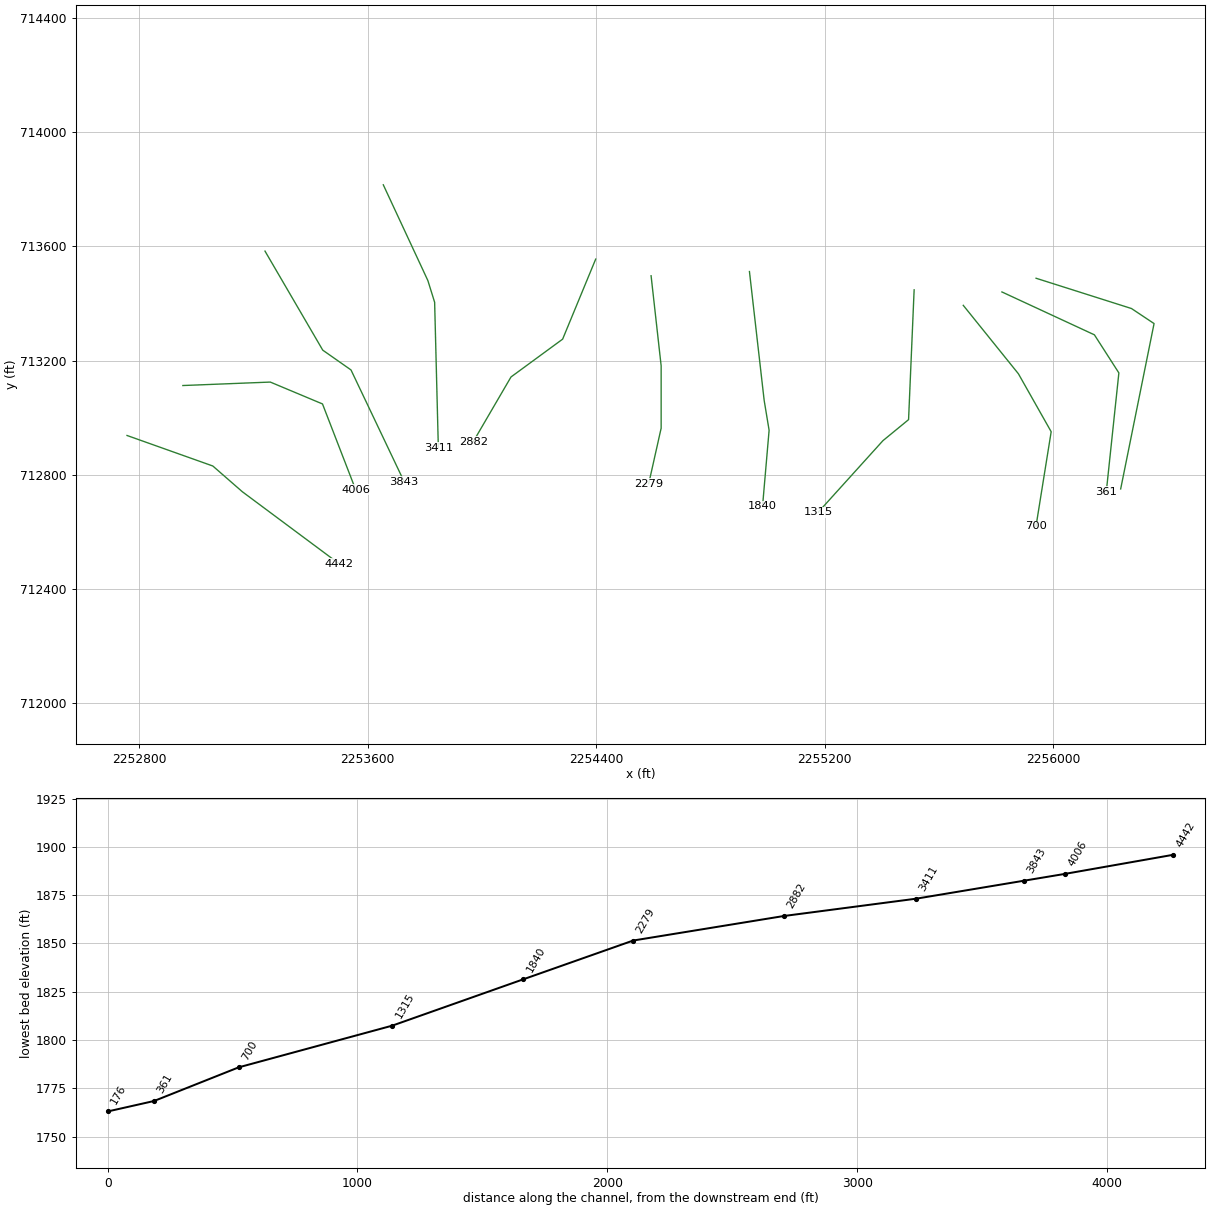
HEC-RAS study BIGLAURLRN.prj: BIGLAURLRN

--- BIGLAURLRN.g01 (geometry) --- (continued)

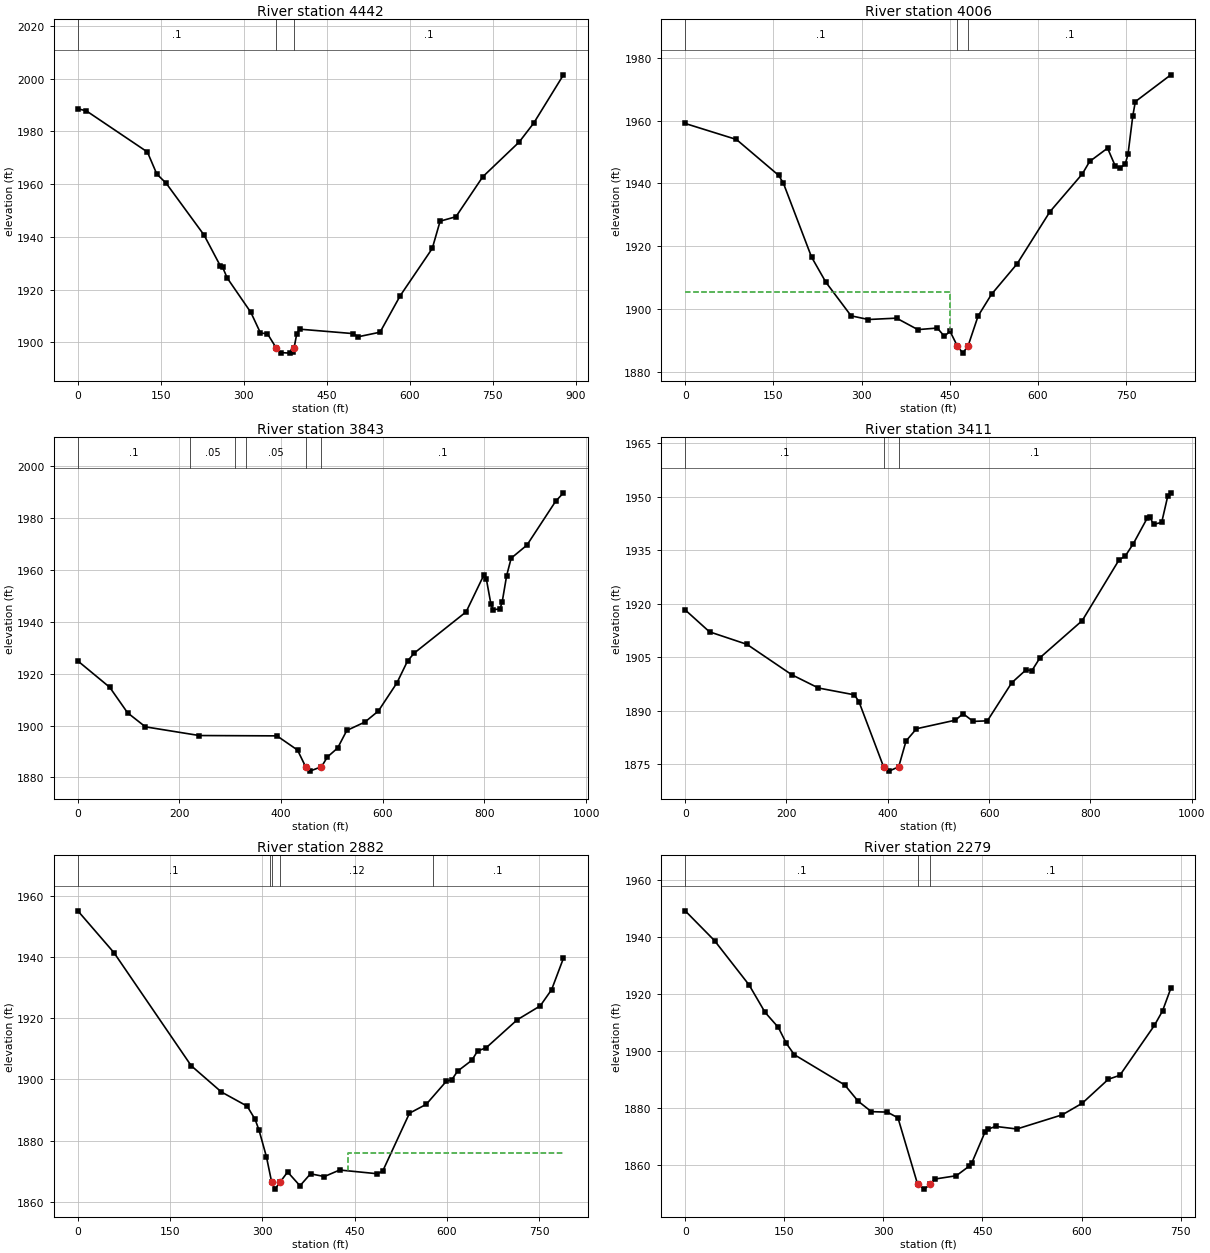
Type RM Length L Ch R = 1 ,4442    ,432.1,435.9,435.8
XS GIS Cut Line= 4
2252757.61839655712938.0439828312253058.06315509 712831.16725116
2253161.21967389712741.2077441262253500.15675864712489.063258657
#Sta/Elev= 30
       0 1988.62    15.5  1987.8   125.8 1972.21   142.8 1963.84   159.8 1960.34
   228.2 1940.71   257.4  1929.1   261.7 1928.52   270.2 1924.37   312.9 1911.34
   330.3 1903.51   342.9 1903.24  358.711897.858   367.2 1896.07   384.2 1895.88
   388.9 1896.38  391.051897.855     396 1903.32   401.2 1904.97   497.9 1903.29
   506.5 1902.07   546.5 1903.82   583.1 1917.71   640.9 1935.59   655.1 1945.95
   683.7 1947.64   732.3 1962.81   798.1 1975.99   824.4 1983.17   878.2 2001.49
#Mann= 3 ,-1,0
       0      .1       0  358.71    .045       0  391.05      .1       0
Bank Sta=358.71,391.05
XS Rating Curve= 0 ,0
Exp/Cntr=0.3,0.1

Type RM Length L Ch R = 1 ,4006    ,165.3,162.5,160.4
XS GIS Cut Line= 4
2252953.17966678713112.9290920782253259.29362929713125.041515055
 2253442.0952743713048.445216047 2253557.9828424 712748.87979203
#Sta/Elev= 30
       0 1959.09    87.1    1954   159.1 1942.54   167.1 1940.01   214.9 1916.52
   239.2 1908.53   282.1 1897.82   311.6 1896.65   359.4 1897.08   395.6 1893.43
   428.7 1893.93   440.6 1891.32   450.4 1892.88  462.351888.343   472.1 1885.94
   481.21888.344   498.1 1897.78   520.9 1904.69   564.4 1914.39     620 1930.94
   675.3 1943.03   687.7 1946.99   718.2 1951.23   731.3 1945.53   739.7 1944.99
   748.2 1946.11     753 1949.37   761.1  1961.5   765.4 1966.05   825.8 1974.59
#Mann= 3 ,-1,0
       0      .1       0  462.35    .045       0   481.2      .1       0
#XS Ineff= 2 , 0
          450.32 1905.34
Permanent Ineff=
       F       F
Bank Sta=462.35,481.2
XS Rating Curve= 0 ,0
Exp/Cntr(USF)=0,0
Exp/Cntr=0.3,0.1

Type RM Length L Ch R = 1 ,3843    ,442,432.1,422.2
XS GIS Cut Line= 4
2253240.73820027713583.6127174132253443.00479632713236.767605445
 2253541.9205699713167.4582712542253728.02069399712776.227853708
#Sta/Elev= 30
       0 1924.92    62.8 1914.75    97.9 1904.92     133 1899.51     239 1896.16
   391.8 1896.03   432.2 1890.57  448.16 1884.14   456.6 1882.44   479.41884.145
   491.1  1887.9   511.2 1891.36   529.2 1898.12   564.7 1901.34   591.3 1905.61
   627.8 1916.45   648.8 1924.93   662.1 1927.98     764 1943.84   798.8 1958.02
   803.9 1956.32   812.7 1946.86   817.2 1944.67   830.5 1944.95   834.9 1947.63
   843.7 1957.82   852.6 1964.53   883.6 1969.56   939.9 1986.41   955.5 1989.72
#Mann= 6 ,-1,0
       0      .1       0     220     .05       0     310      .1       0
     330     .05       0  448.16    .045       0   479.4      .1       0
Bank Sta=448.16,479.4
XS Rating Curve= 0 ,0
Exp/Cntr=0.3,0.1

Type RM Length L Ch R = 1 ,3411    ,543.4,529.2,513.8
XS GIS Cut Line= 4
2253654.97230842713815.6925859892253811.01841277713480.536751485
2253834.74147211713404.4446703532253847.71667851 712895.09459906
#Sta/Elev= 30
       0 1918.28      48 1912.14   121.9 1908.64   210.5 1900.12   263.1 1896.41
     334  1894.5     343 1892.61  391.711874.346   402.5 1873.13  421.561874.346
   436.1 1881.59   456.7    1885   533.4  1887.4   548.7 1889.21   568.7 1887.05
   596.7 1887.22   644.7 1897.87   672.7 1901.46   684.7 1901.31   700.8 1904.93
   783.9 1915.28   856.8 1932.33   868.8 1933.33   884.8 1936.82   912.8 1944.13
   916.8 1944.38   924.8 1942.25   940.8 1942.78   952.8 1950.16   958.9 1951.07
#Mann= 3 ,-1,0
       0      .1       0  391.71    .045       0  421.56      .1       0
Bank Sta=391.71,421.56
XS Rating Curve= 0 ,0
Exp/Cntr=0.3,0.1

Type RM Length L Ch R = 1 ,2882    ,593.4,602.8,607.8
XS GIS Cut Line= 4
2254398.67466047713555.5546134672254282.93532232713275.350866338
2254102.14900029 713142.890443692253970.06977332712916.515128066
#Sta/Elev= 30
       0 1955.02    58.8 1941.35   184.3 1904.45   233.4 1895.88   275.2 1891.26
   288.2 1886.93   294.7 1883.31   306.6 1874.71  314.991866.529   320.4 1864.17
  328.981866.504     341 1869.77   361.1 1865.26   378.2 1869.17   400.8 1868.28
   425.6 1870.41     487 1869.19   495.6 1870.07   539.1 1888.96   566.3 1891.85
   598.7 1899.32     608 1899.93   617.3 1902.68   640.4 1906.22   649.9 1909.28
   663.6 1910.29   714.2 1919.45   751.6 1923.99   770.1 1929.28   789.4 1939.58
#Mann= 5 ,-1,0
       0      .1       0  313.17     .12       0  314.99    .045       0
  328.98     .12       0  577.29      .1       0
#XS Ineff= 2 , 0
                          439.01         1875.81
Permanent Ineff=
       F       F
Bank Sta=314.99,328.98
XS Rating Curve= 0 ,0
Exp/Cntr=0.3,0.1

Type RM Length L Ch R = 1 ,2279    ,434,439.7,445.2
XS GIS Cut Line= 4
2254592.64741193713497.3081991812254627.89160731713181.788735729
2254627.89160731712963.6103833422254584.25593684712768.928161211
#Sta/Elev= 30
       0 1949.11    44.4 1938.66    96.7 1923.12   120.9  1913.5     141 1908.22
   153.1 1902.62   165.1 1898.66   241.6 1888.01   261.7 1882.36   281.9 1878.65
     306  1878.5   322.1 1876.49  351.871853.173   362.1 1851.48  370.941853.173
   378.1 1855.02   410.4 1856.18   430.1 1859.57   434.1  1860.8   454.1 1871.61
   458.4 1872.51   469.8 1873.48   502.1 1872.58   570.9 1877.56   601.1 1881.62
   640.6 1890.03     658 1891.41   710.3 1908.91   722.6 1913.99   735.2 1921.94
#Mann= 3 ,-1,0
       0      .1       0  351.87    .045       0  370.94      .1       0
Bank Sta=351.87,370.94
XS Rating Curve= 0 ,0
Exp/Cntr(USF)=0,0
Exp/Cntr=0.3,0.1

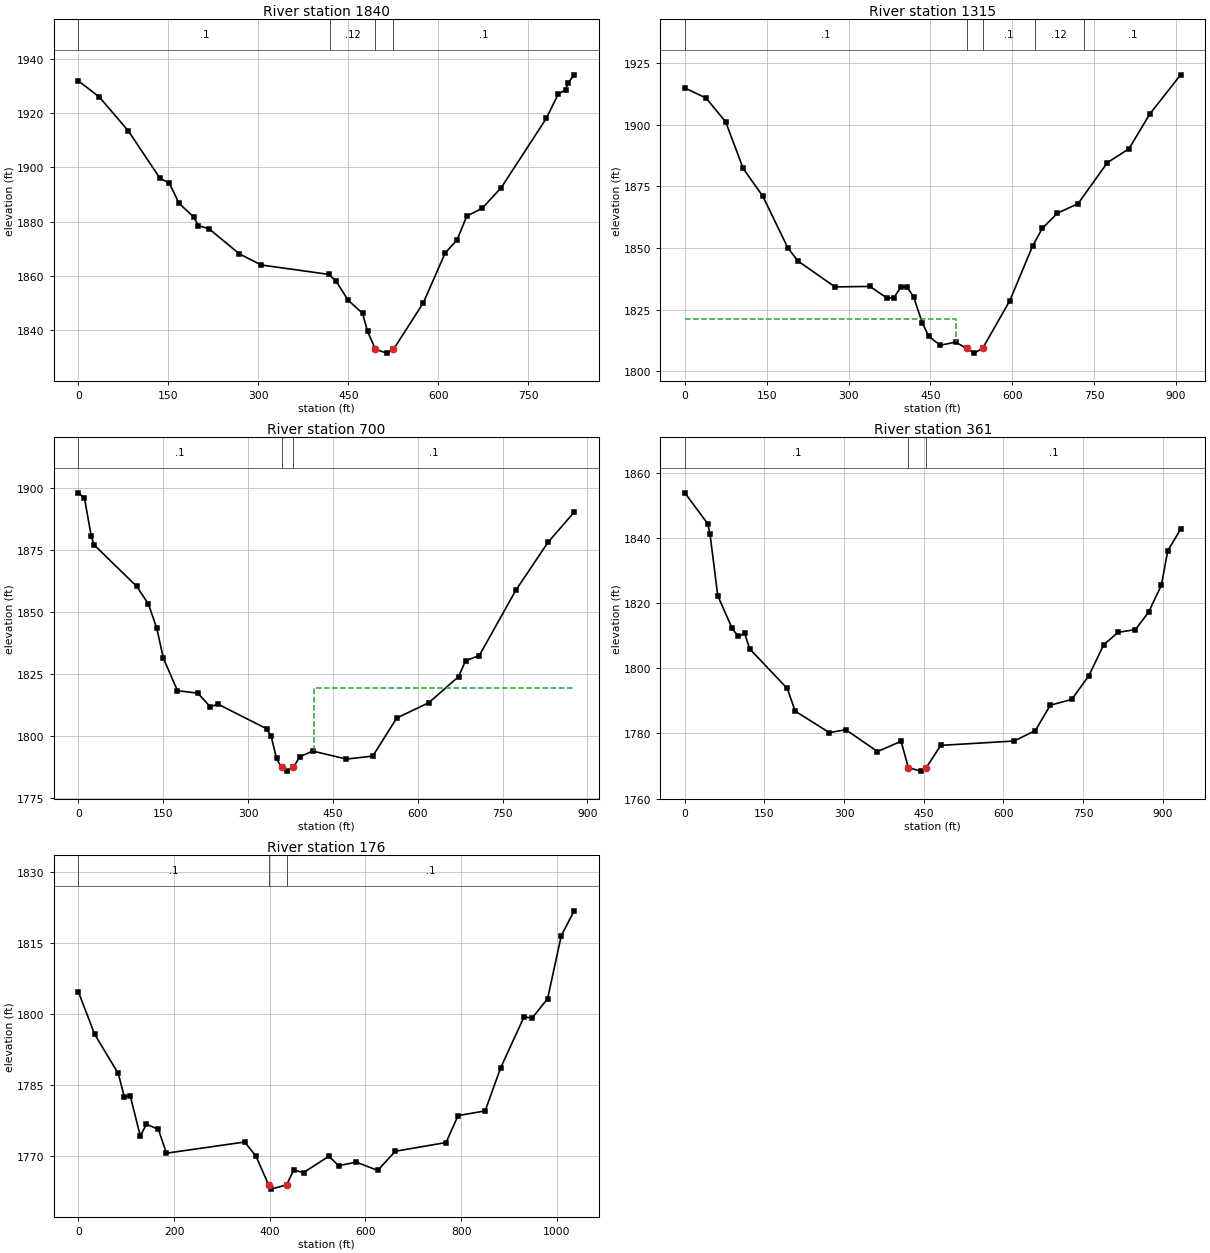
Type RM Length L Ch R = 1 ,1840    ,539,525,508.2
XS GIS Cut Line= 4
2254937.07660957713512.023939769     2254988.549713061.280689628
2255005.87885274712956.2936425392254982.96400004712690.817103388
#Sta/Elev= 30
       0 1931.97    35.1 1925.98    83.4 1913.46   135.7  1896.1   151.8 1894.12
   167.9 1886.72   192.1 1881.73   200.1  1878.5   217.9 1877.33   268.6 1868.05
   304.8 1863.97   417.9 1860.48   429.6    1858   449.7 1850.97   473.7 1846.14
   482.2 1839.41  495.321832.796   514.6 1831.42  525.321832.797   575.3 1850.09
   611.4 1868.36   631.5 1873.32   647.5 1882.03   672.9 1884.87     705 1892.54
     780 1918.07   800.1 1927.14   812.2 1928.64   816.1 1931.11   826.5 1934.19
#Mann= 4 ,-1,0
       0      .1       0     420     .12       0  495.32    .045       0
  525.32      .1       0
Bank Sta=495.32,525.32
XS Rating Curve= 0 ,0
Exp/Cntr=0.3,0.1

Type RM Length L Ch R = 1 ,1315    ,591.7,614.6,632
XS GIS Cut Line= 4
     2255513.718      713448.0062255494.23940745712993.530252375
 2255404.3868776712919.7745534572255178.24129312712669.727846494
#Sta/Elev= 30
       0 1914.94    38.9 1910.84    74.9 1901.17   106.9 1882.29     143    1871
   188.5  1850.2     207 1844.81   275.1 1834.26   339.1 1834.46   371.2  1829.6
   383.2 1829.94   395.8 1834.15   407.2 1834.15   419.2 1830.18   435.2 1819.59
   447.2 1814.16   467.9 1810.61   496.4 1811.86  516.251809.302     530 1807.41
  545.511809.304   595.3 1828.64   637.1 1850.83   654.9    1858   682.5 1864.12
   720.4 1868.02   774.2 1884.66   813.8  1890.3   851.7 1904.32   908.3 1920.25
#Mann= 5 ,-1,0
       0      .1       0  516.25    .045       0  545.51      .1       0
  641.14     .12       0  731.14      .1       0
#XS Ineff= 2 , 0
          496.82 1821.28
Permanent Ineff=
       F       F
Bank Sta=516.25,545.51
XS Rating Curve= 0 ,0
Exp/Cntr=0.3,0.1

Type RM Length L Ch R = 1 ,700     ,335.7,338.5,339.5
XS GIS Cut Line= 4
2255685.80009903713393.649916958 2255878.8341935713154.077201771
2255993.57921383712951.2087986332255940.31521686712619.470886246
#Sta/Elev= 30
       0 1898.24    10.9 1896.07    22.9 1880.63    27.6 1877.28   103.3 1860.43
   123.9 1853.34   138.6 1843.62   150.4  1831.4   175.3 1818.32   211.2 1817.33
   233.3 1811.85   247.2 1812.86   332.8 1802.97   340.9 1799.98   350.4 1790.94
  359.251787.325   368.4 1785.83  380.291787.327   391.6 1791.67   414.4 1793.93
   474.1  1790.7   520.6  1791.9     563 1807.28   619.8 1813.48   672.4 1824.01
   684.6 1830.41   708.9 1832.48   773.7 1858.95   830.4 1878.22   876.7 1890.44
#Mann= 3 ,-1,0
       0      .1       0  359.25    .045       0  380.29      .1       0
#XS Ineff= 2 , 0
                          416.61         1819.41
Permanent Ineff=
       F       F
Bank Sta=359.25,380.29
XS Rating Curve= 0 ,0
Exp/Cntr(USF)=0,0
Exp/Cntr=0.3,0.1

Type RM Length L Ch R = 1 ,361     ,182.5,185.9,197.2
XS GIS Cut Line= 4
2255821.08466331713440.5916421442256144.96035765713290.449691509
2256230.60375243713157.0906910572256186.55857797712741.108487813
#Sta/Elev= 30
       0 1853.77    43.1 1844.32    47.5 1841.08    62.1 1822.19    89.2  1812.2
   100.4 1809.75   112.7 1810.65   122.2 1805.91     193 1793.77   207.8 1786.83
   272.3 1780.23   303.2 1781.13   362.9 1774.42   407.3 1777.57  420.991769.523
   444.1 1768.42  454.871769.525   482.1 1776.32     620 1777.65   660.2 1780.85
   688.3 1788.64   728.6 1790.41   760.8 1797.62   788.9 1807.17   815.9 1810.98
   848.6 1811.82   873.4 1817.15   897.5 1825.42   909.6 1836.01   933.8 1842.61
#Mann= 3 ,-1,0
       0      .1       0  420.99    .045       0  454.87      .1       0
Bank Sta=420.99,454.87
XS Rating Curve= 0 ,0
Exp/Cntr(USF)=0,0
Exp/Cntr=0.3,0.1

Type RM Length L Ch R = 1 ,176     ,,,
XS GIS Cut Line= 4
2255940.70614771713488.5442230662256274.83174005713382.516476845
2256353.83556947 713329.889100142256236.90994597712750.787550841
#Sta/Elev= 30
       0 1804.68    34.1 1795.69    83.4 1787.42      96 1782.53   108.6 1782.65
   129.5  1774.2   142.1 1776.68   167.3 1775.62   184.1 1770.58   347.8 1772.94
   371.4 1769.91  397.671763.912   403.5 1762.99  435.291763.914   450.3 1767.03
   470.7 1766.49   523.7 1769.93   544.1 1767.94   580.9  1768.7   625.7 1766.94
   662.5 1770.99   768.6 1772.83   793.8 1778.53   850.2  1779.5   882.8 1788.64
   931.8 1799.42   948.1 1799.07   980.8 1803.21  1009.3 1816.49  1036.3 1821.76
#Mann= 3 ,-1,0
       0      .1       0  397.67    .045       0  435.29      .1       0
Bank Sta=397.67,435.29
XS Rating Curve= 0 ,0
Exp/Cntr(USF)=0,0
Exp/Cntr=0.3,0.1
LCMann Table=0

Chan Stop Cuts=-1
Use User Specified Reach Order=0
Composite Channel Slope=5